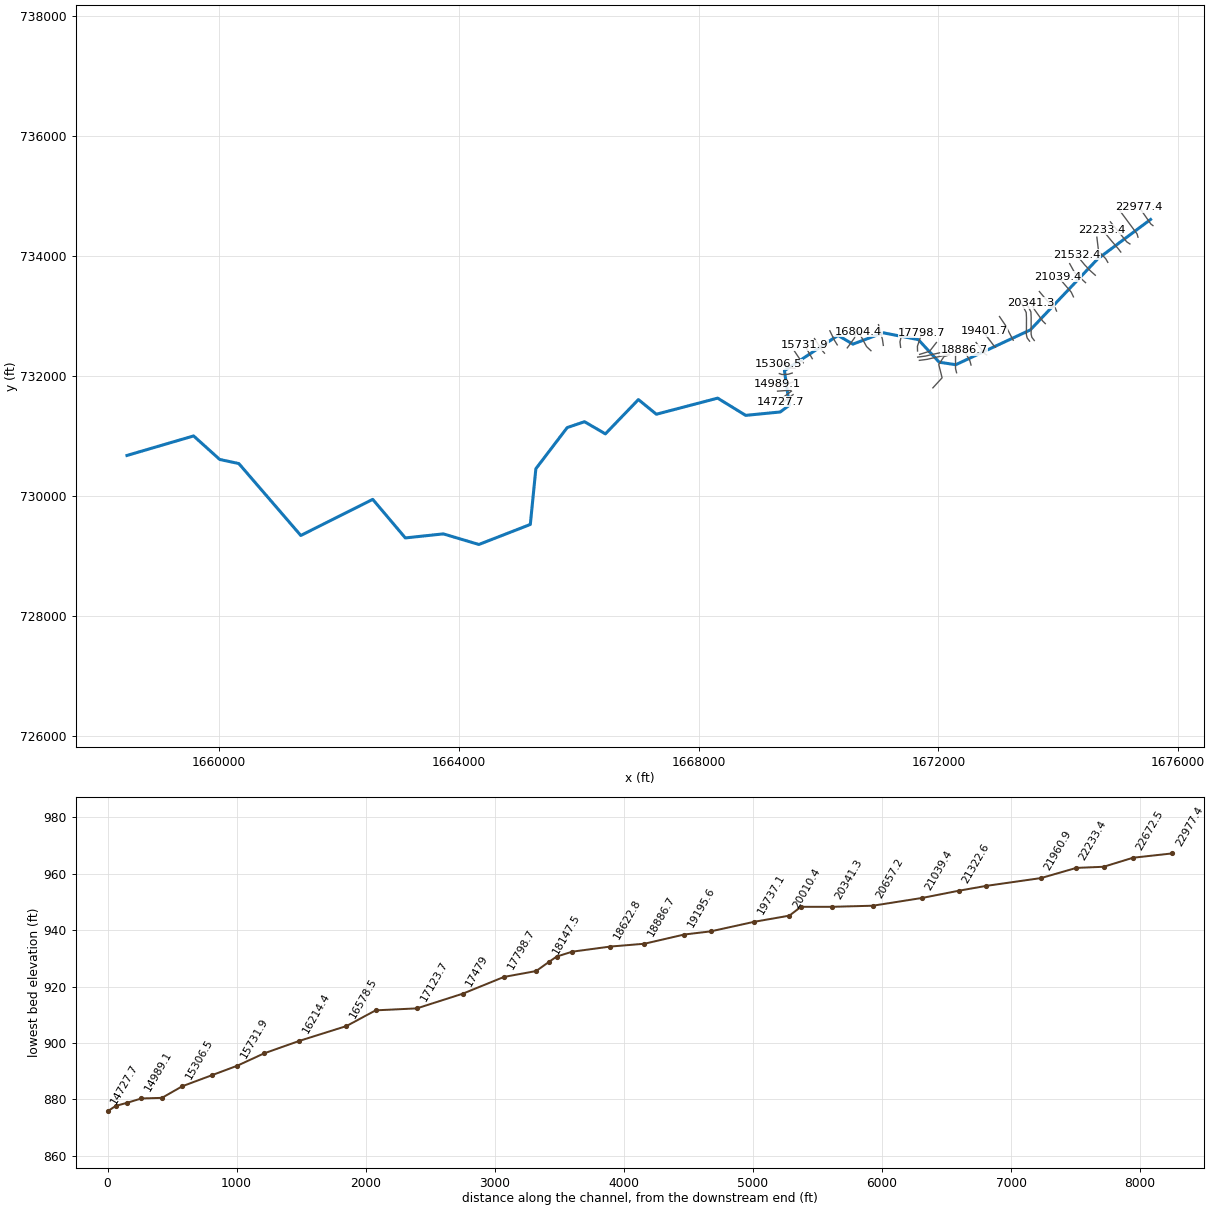
--- HARDINRUN.prj (project) ---

Proj Title=HARDINRUN
Current Plan=p01
Default Exp/Contr=0,0
English Units
Geom File=g01
Flow File=f01
Plan File=p01
BEGIN DESCRIPTION:
END DESCRIPTION:
DSS Export Rating Curves= 0
DSS Export Rating Curve Sorted= 0
DSS Export Volume Flow Curves= 0
DXF Filename=..\..\..\..\..\Engineering\Hydraulics\HARDINRUN\HARDINRUN.
DXF OffsetX= 0
DXF OffsetY= 0
DXF ScaleX= 0
DXF ScaleY= 0

--- HARDINRUN.p01 (plan) ---

Plan Title=Floodplain
Program Version=4.00
Geom File=g01
Flow File=f01
K Sum by GR=0
Std Step Tol=0.01
Critical Tol=0.01
Num of Std Step Trials=20
Max Error Tol=0.3
Flow Tol Ratio=0.001
Split Flow NTrial=30
Split Flow Tol=0.02
Split Flow Ratio=0.02
Log Output Level=0
Friction Slope Method=1
Unsteady Friction Slope Method=2
Unsteady Bridges Friction Slope Method=1
Global Log Level=0
CheckData=False
Run HTab=0
Run UNet=0
Run PostProcess=0
UNET Theta=0
UNET Theta Warmup=0
UNET ZTol=0
UNET ZSATol=0
UNET MxIter=0
UNET MaxInSteps=0
UNET DtIC=0
UNET DtMin=0
UNET MaxCRTS=0
UNET WFStab=0
UNET SFStab=0
UNET WFX=0
UNET SFX=0
UNET DSS MLevel=0
UNET DZMax Abort=0
UNET Convert EG Bridges=0
UNET Use Existing IB Tables=0
UNET Froude Limit=0
UNET Froude Power=0
Write IC File=0
Echo Input=False
Echo Output=False
Write Detailed=0

--- HARDINRUN.f01 (steady flow) ---

Flow Title=NFF Regression Equation
Program Version=4.10
Number of Profiles= 1
Profile Names=P100yr
River Rch & RM=HARDINRUN,Main            ,22977.4
 1067.63
River Rch & RM=HARDINRUN,Main            ,20341.3
1174.781
River Rch & RM=HARDINRUN,Main            ,19737.1
1285.329
River Rch & RM=HARDINRUN,Main            ,18207
1405.993
River Rch & RM=HARDINRUN,Main            ,15731.9
1490.958
River Rch & RM=HARDINRUN,Main            ,15306.5
1663.356
River Rch & RM=HARDINRUN,Main            ,10360
1773.655
River Rch & RM=HARDINRUN,Main            ,10058.4
1984.792
Boundary for River Rch & Prof#=HARDINRUN,Main            , 1
Up Type= 0
Dn Type= 3
Dn Slope=0.02
DSS Import GetInterval= 0
DSS Import GetPeak= 0
DSS Import FillOption= 0

--- HARDINRUN.g01 (geometry) ---

Geom Title=USGS 10m DEM
Program Version=4.10

River Reach=HARDINRUN       ,Main
Reach XY= 30
      1675539.88       734607.47     1674654.347      733947.682
     1673533.931      732767.274     1672289.616      732187.565
     1672013.792       732229.08     1671665.875      732605.469
      1671079.07      732719.358     1670574.209      732530.469
     1670325.598      732675.608     1669432.542      732088.108
      1669515.09      731513.018     1669362.403      731399.913
     1668786.014      731343.663     1668318.653      731630.469
     1667296.431      731362.413     1666997.125      731606.858
     1666446.431       731035.33     1666098.514      731237.813
     1665809.625      731140.191     1665286.622       730454.08
     1665194.308       729526.23     1664336.032      729192.605
     1663743.382      729369.276     1663109.539      729301.736
     1662566.005      729944.151     1661365.879      729342.823
     1660332.528       730540.58     1660013.532       730609.04
     1659578.289      731000.955     1658466.726      730675.664

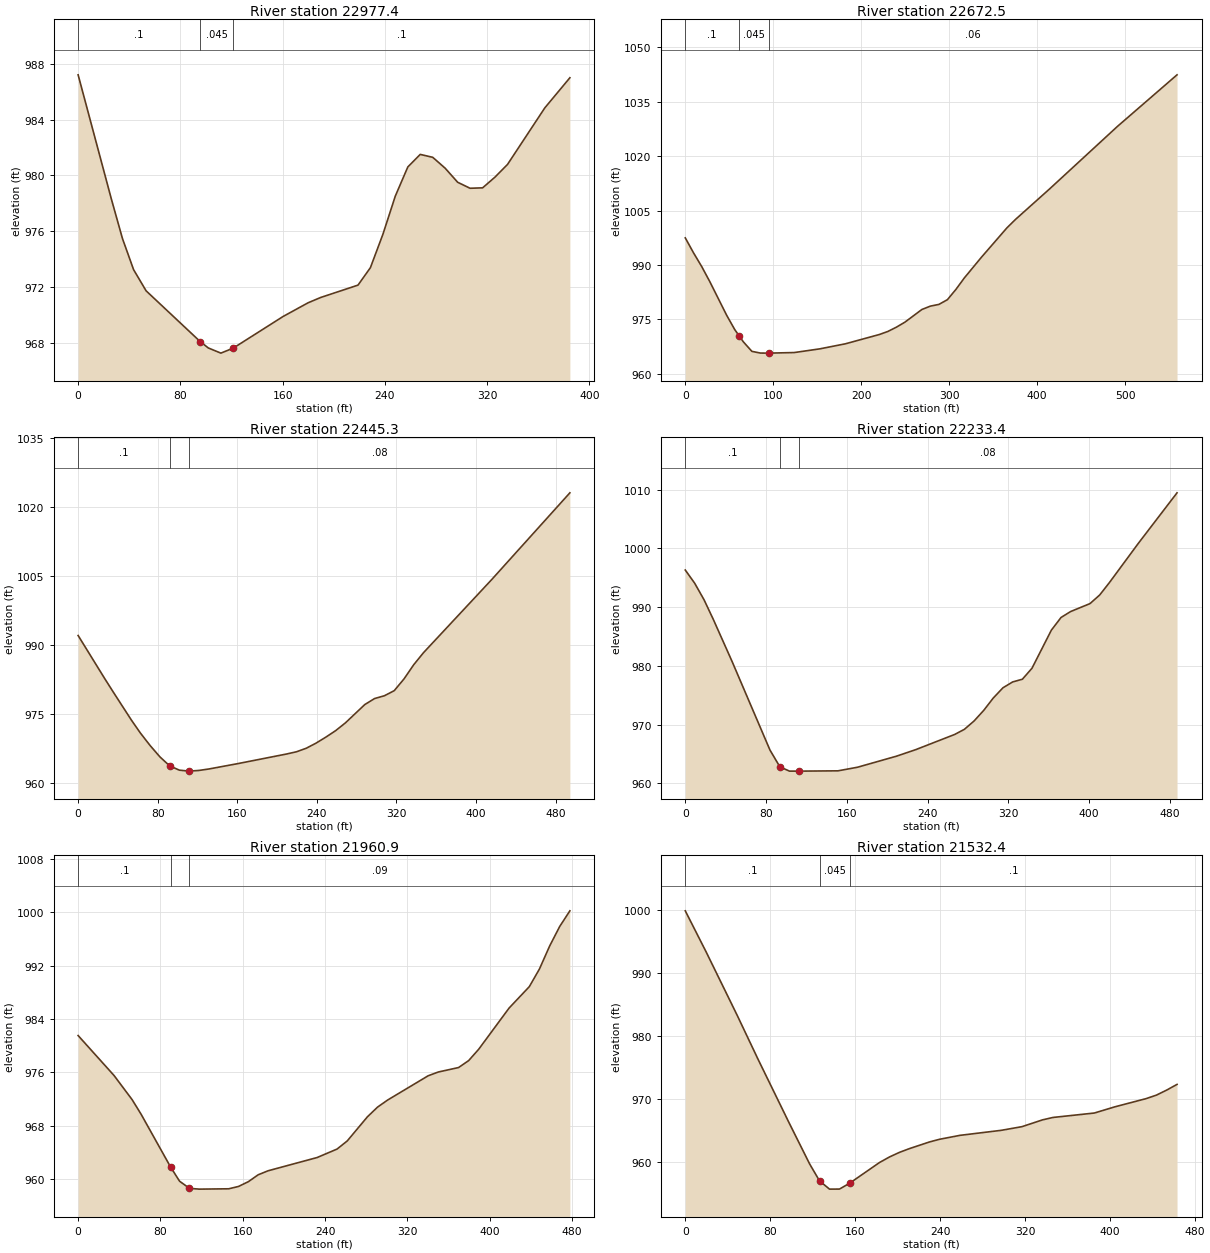
Type RM Length L Ch R = 1 ,22977.4 ,307.8,304.9,304.3
XS GIS Cut Line= 3
      1675579.01      734505.109     1675544.288      734531.151
     1675348.975      734811.099
#Sta/Elev= 27
       0  987.21      26   978.3    34.7  975.46    43.4  973.23    53.2  971.71
    95.5  968.07   101.9  967.61   111.7  967.24   121.4   967.6   160.4  969.87
   179.9  970.85   189.7  971.23     219  972.12   228.7  973.37   238.5  975.77
   248.2  978.51     258   980.6   267.7   981.5   277.5  981.29   287.2  980.51
     297   979.5   306.7  979.07   316.5   979.1   326.2  979.87     336  980.78
   365.2  984.84   384.8     987
#Mann= 3 , 0 , 0
       0      .1       0    95.5    .045       0   121.4      .1       0
Bank Sta=95.5,121.4
XS Rating Curve= 0 ,0
Exp/Cntr=0.3,0.1

Type RM Length L Ch R = 1 ,22672.5 ,222.5,227.3,227.6
XS GIS Cut Line= 3
     1675329.444      734311.967     1675314.253       734366.22
     1675014.774      734769.866
#Sta/Elev= 30
       0  997.49     9.4  993.35    18.8  989.53    28.2  985.27      47  976.16
    56.3  972.17    61.2  970.48      66  968.82    75.7  966.19    85.3  965.72
      95   965.7     124  965.86     153  966.88     182  968.27   220.7  970.84
   230.3  971.68     240  972.86   249.6  974.23     269  977.74   278.6  978.66
   288.3  979.14     298  980.44   307.6  983.26   317.3  986.46   336.6  992.13
   365.6 1000.24   375.3 1002.56     414 1010.96   491.3 1028.24     559 1042.46
#Mann= 3 , 0 , 0
       0      .1       0    61.2    .045       0      95     .06       0
Bank Sta=61.2,95
XS Rating Curve= 0 ,0
Exp/Cntr=0.3,0.1

Type RM Length L Ch R = 1 ,22445.3 ,211.4,211.8,208.3
XS GIS Cut Line= 3
     1675194.895      734199.119     1675142.812      734233.842
     1674869.375      734568.043
#Sta/Elev= 29
       0  992.05    26.8  982.64    35.8  979.57    53.6  973.61    62.6   970.8
    72.4  968.07    82.2  965.61      92  963.65   101.8  962.71   111.7   962.5
   121.5  962.65   131.3  962.96   160.7  964.14   209.8  966.24   219.6  966.72
   229.4  967.49   239.2   968.6   249.1  969.91   258.9  971.32   268.7  973.01
   288.3  977.02   298.1  978.32   307.9  978.92   317.8  980.03   327.6  982.58
   337.4  985.68   347.2   988.3   415.9 1004.26   494.4 1023.14
#Mann= 3 , 0 , 0
       0      .1       0      92    .045       0   111.7     .08       0
Bank Sta=92,111.7
XS Rating Curve= 0 ,0
Exp/Cntr=0.3,0.1

Type RM Length L Ch R = 1 ,22233.4 ,270.5,272.5,273.4
XS GIS Cut Line= 4
     1675042.986      734064.571     1674997.413      734123.165
     1674878.055      734262.053     1674732.656      734440.005
#Sta/Elev= 30
       0  996.32     9.3  994.08    18.6  991.26    27.8  987.91    46.4  980.75
    83.9  965.69    93.7  962.84   103.2   962.1   112.8   962.1   151.3  962.15
   170.6  962.76   209.2  964.64   228.4  965.76   266.9  968.34   276.5  969.21
   286.1  970.63   295.7  972.44   305.2  974.55   314.8  976.29   324.4  977.28
     334  977.74   343.5  979.61   362.7  986.09   372.3  988.25   381.8  989.26
     401  990.61   410.6  992.08   420.1  994.16   448.9 1000.87   487.2 1009.46
#Mann= 3 , 0 , 0
       0      .1       0    93.7    .045       0   112.8     .08       0
Bank Sta=93.7,112.8
XS Rating Curve= 0 ,0
Exp/Cntr=0.3,0.1

Type RM Length L Ch R = 1 ,21960.9 ,405.3,428.5,426
XS GIS Cut Line= 4
     1674825.972       733893.13      1674791.25      733953.894
     1674671.892      734077.592      1674643.68      734311.967
#Sta/Elev= 30
       0  981.54      35  975.53    52.5  971.92    61.2  969.74    89.9  961.81
    98.6  959.69   108.2  958.62   117.7   958.5   146.4  958.55   155.9   958.9
   165.5  959.62     175  960.65   184.6  961.25   232.3  963.24   251.7  964.51
   261.6  965.73   281.2  969.35   291.1  970.81   300.9  971.87   340.2   975.5
   350.1  976.07   369.8  976.74   379.6  977.78   389.4  979.49   418.9  985.66
   438.6  988.88   448.4  991.52   458.3  994.96   468.1   997.9     478 1000.25
#Mann= 3 , 0 , 0
       0      .1       0    89.9    .045       0   108.2     .09       0
Bank Sta=89.9,108.2
XS Rating Curve= 0 ,0
Exp/Cntr=0.3,0.1

Type RM Length L Ch R = 1 ,21532.4 ,207.9,209.8,210.8
XS GIS Cut Line= 4
     1674617.639      733678.286     1674537.343      733749.901
     1674439.687      733851.897     1674302.968      734016.828
#Sta/Elev= 28
       0  999.81    19.6  993.31    39.1  986.61    48.9  983.24    68.5  976.29
    97.8  966.19     117  959.72   126.4  957.01   135.8   955.7   145.2  955.71
   154.7  956.63   182.9  959.92   192.3   960.8   201.7  961.53   211.2  962.13
     230  963.18   239.4   963.6   258.5  964.22   297.5  965.02     317   965.6
   336.4  966.68   346.2  967.06   385.1  967.76   404.6  968.75   433.8  970.04
   443.6   970.6   453.3   971.4     463   972.3
#Mann= 3 , 0 , 0
       0      .1       0   126.4    .045       0   154.7      .1       0
Bank Sta=126.4,154.7
XS Rating Curve= 0 ,0
Exp/Cntr=0.3,0.1

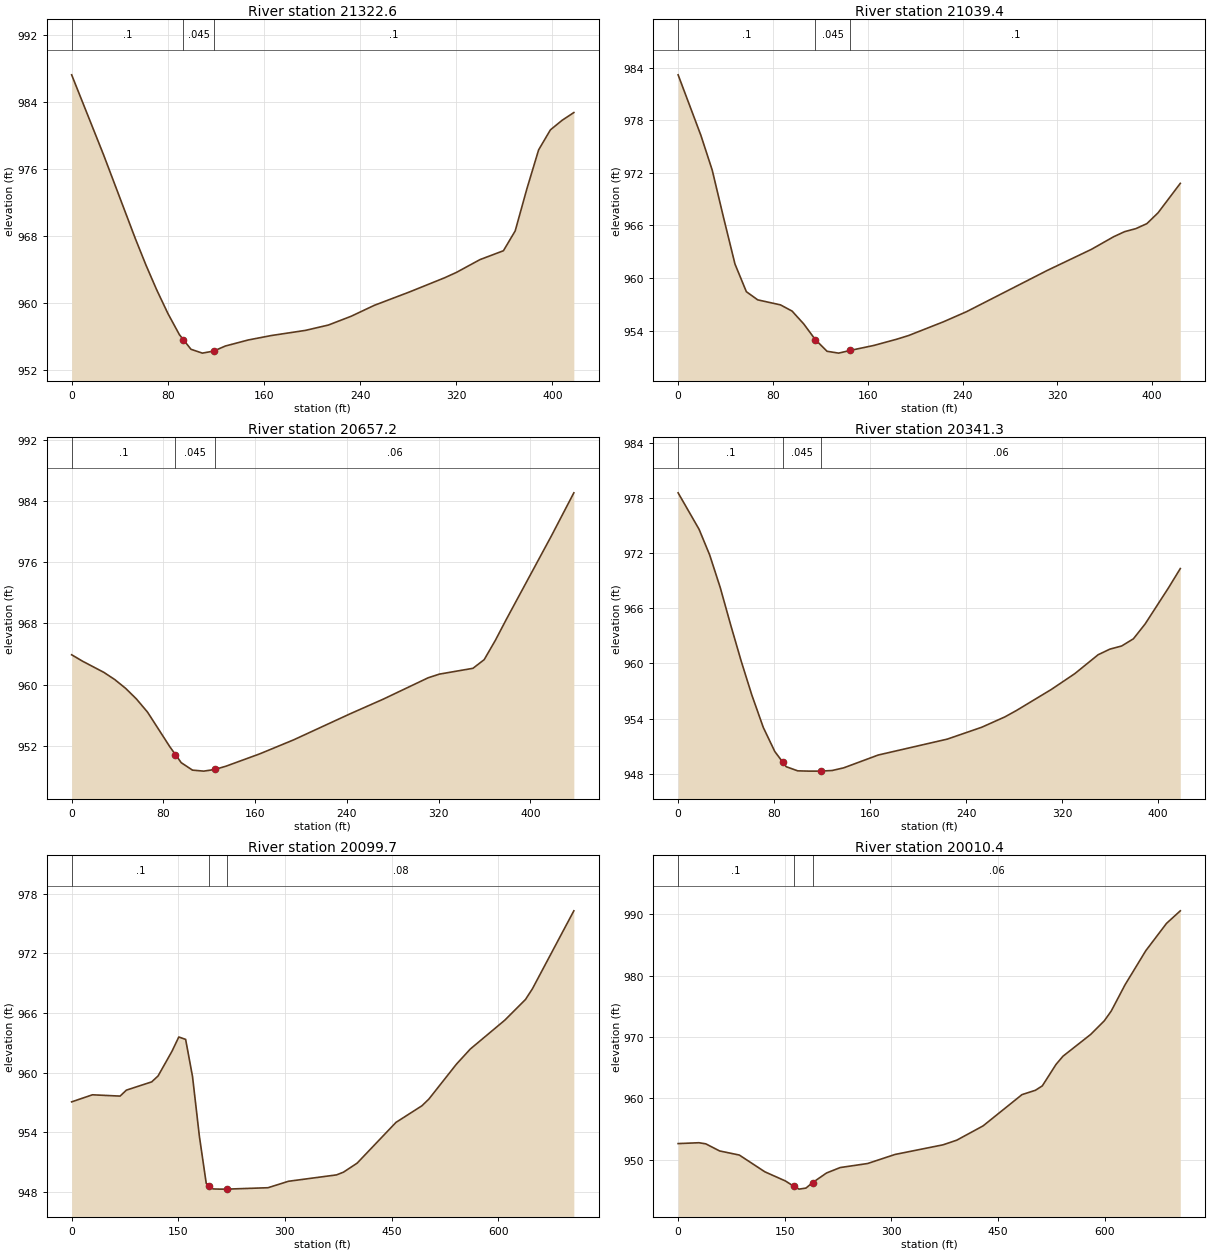
Type RM Length L Ch R = 1 ,21322.6 ,284.6,283.1,279.6
XS GIS Cut Line= 4
     1674454.878      733554.588     1674402.795      733602.331
     1674270.416      733726.029     1674190.121      733871.428
#Sta/Elev= 29
       0  987.27    26.5  977.73      53  967.69    61.8  964.54    70.6  961.62
    80.2  958.71    89.7   956.2    92.9  955.62    99.3  954.46   108.8     954
   118.3  954.25   127.9  954.85   146.9  955.57     166   956.1   194.6  956.72
   213.7  957.36   232.8  958.42   251.8  959.71   281.1  961.31   310.4  963.01
   320.2  963.65   339.8  965.18   359.3  966.24   369.1  968.61   378.8  973.63
   388.6   978.3   398.4  980.69   408.2  981.84   417.9  982.76
#Mann= 3 , 0 , 0
       0      .1       0    92.9    .045       0   118.3      .1       0
Bank Sta=92.9,118.3
XS Rating Curve= 0 ,0
Exp/Cntr=0.3,0.1

Type RM Length L Ch R = 1 ,21039.4 ,379.3,382.2,385.3
XS GIS Cut Line= 4
     1674253.055      733318.043     1674216.163      733396.168
     1674081.614      733552.418     1673999.149      733654.415
#Sta/Elev= 27
       0  983.17    19.2  976.28    28.8   972.3    38.4  966.87      48   961.6
    57.6  958.45    67.2  957.52    86.4  956.95    96.2  956.24     106  954.78
   115.8  952.99   125.7  951.66   135.5  951.45   145.3  951.76     165  952.32
   184.6  953.04   194.4  953.45   223.9  955.02   243.5  956.18   311.3  960.86
   348.8  963.28   367.6  964.72   376.9   965.3   386.3  965.64   395.6  966.21
     405  967.44   423.8   970.8
#Mann= 3 , 0 , 0
       0      .1       0   115.8    .045       0   145.3      .1       0
Bank Sta=115.8,145.3
XS Rating Curve= 0 ,0
Exp/Cntr=0.3,0.1

Type RM Length L Ch R = 1 ,20657.2 ,321.4,316,306.7
XS GIS Cut Line= 4
     1673970.937      733081.498     1673949.236      733133.581
     1673810.347      733257.279     1673684.479      733407.019
#Sta/Elev= 26
       0   963.9     9.4  963.07    28.2  961.59    37.6  960.66      47  959.52
    56.4  958.14    66.2   956.4    85.8  951.84    90.5  950.86    95.6  949.79
   105.4  948.82   115.2  948.69     125  948.91   134.7  949.34   164.1  950.95
   193.5  952.77   242.4  956.15   271.8   958.1   310.9  960.89   320.7  961.37
     350  962.13   359.8  963.26   369.6   965.8   379.3  968.58   418.5  979.46
     438  985.07
#Mann= 3 , 0 , 0
       0      .1       0    90.5    .045       0     125     .06       0
Bank Sta=90.5,125
XS Rating Curve= 0 ,0
Exp/Cntr=0.3,0.1

Type RM Length L Ch R = 1 ,20341.3 ,258.5,241.5,224.1
XS GIS Cut Line= 4
     1673783.799      732871.935     1673740.396      732915.338
     1673605.847      733101.969     1673547.254      733214.817
#Sta/Elev= 30
       0  978.55    17.5  974.58    26.3   971.8    35.1  968.26    43.8   964.2
    52.6  960.25    61.4  956.59      71  953.05    80.6  950.43    87.4  949.25
    90.1  948.78    99.7  948.33   109.3   948.3   118.9   948.3   128.5  948.37
   138.1  948.66   166.8  950.05   224.4  951.78   253.1  953.07   272.3  954.19
   281.9  954.88     311  957.17   330.6  958.89   350.1  960.95   359.9  961.56
   369.7   961.9   379.5  962.68   389.3   964.3   408.8  968.23   418.6  970.32
#Mann= 3 , 0 , 0
       0      .1       0    87.4    .045       0   118.9     .06       0
Bank Sta=87.4,118.9
XS Rating Curve= 0 ,0
Exp/Cntr=0.3,0.1

Type RM Length L Ch R = 1 ,20099.7 ,86.3,89.3,91.2
XS GIS Cut Line= 6
     1673599.843      732591.046     1673558.611        732645.3
     1673547.254      732697.456      1673547.76      732977.331
      1673543.42      733068.477     1673443.593      733257.279
#Sta/Elev= 30
       0  957.07    29.2  957.78    68.1  957.65      77  958.25   112.6  959.08
   121.5  959.67     141  962.14   150.7  963.59   160.3  963.35     170  959.62
   179.6  953.64   189.3  948.87   193.7  948.62   198.9  948.32   208.6   948.3
   218.2   948.3   276.1  948.44     305  949.09   372.5  949.73   382.2     950
   401.5  950.91   456.2  955.01   492.7  956.68   502.4  957.35   541.3  960.87
   560.7  962.38   609.2  965.28   638.3  967.36     648  968.43   706.3  976.27
#Mann= 3 , 0 , 0
       0      .1       0   193.7    .045       0   218.2     .08       0
Bank Sta=193.7,218.2
XS Rating Curve= 0 ,0
Exp/Cntr=0.3,0.1

Type RM Length L Ch R = 1 ,20010.4 ,261,273.3,284.5
XS GIS Cut Line= 6
     1673521.718      732580.196     1673480.486      732634.449
     1673468.261      732687.039     1673469.635       732966.48
     1673465.295      733057.626     1673365.468      733246.428
#Sta/Elev= 30
       0   952.6    29.2  952.74    38.9  952.56    58.4   951.4    86.1  950.73
   122.1  947.99   150.8  946.51   162.7  945.64   170.1  945.17   179.8  945.34
   189.4  946.25   208.7   947.8     228  948.69   266.6  949.35   305.2  950.83
   372.7   952.4     392  953.16     429  955.49   483.7  960.59   502.6   961.3
   512.3  962.02   531.7  965.54   541.4  966.86   580.2   970.4   599.6  972.65
   609.3  974.24   628.8  978.54   657.9  984.08     687  988.53   706.4  990.58
#Mann= 3 , 0 , 0
       0      .1       0   162.7    .045       0   189.4     .06       0
Bank Sta=162.7,189.4
XS Rating Curve= 0 ,0
Exp/Cntr=0.3,0.1

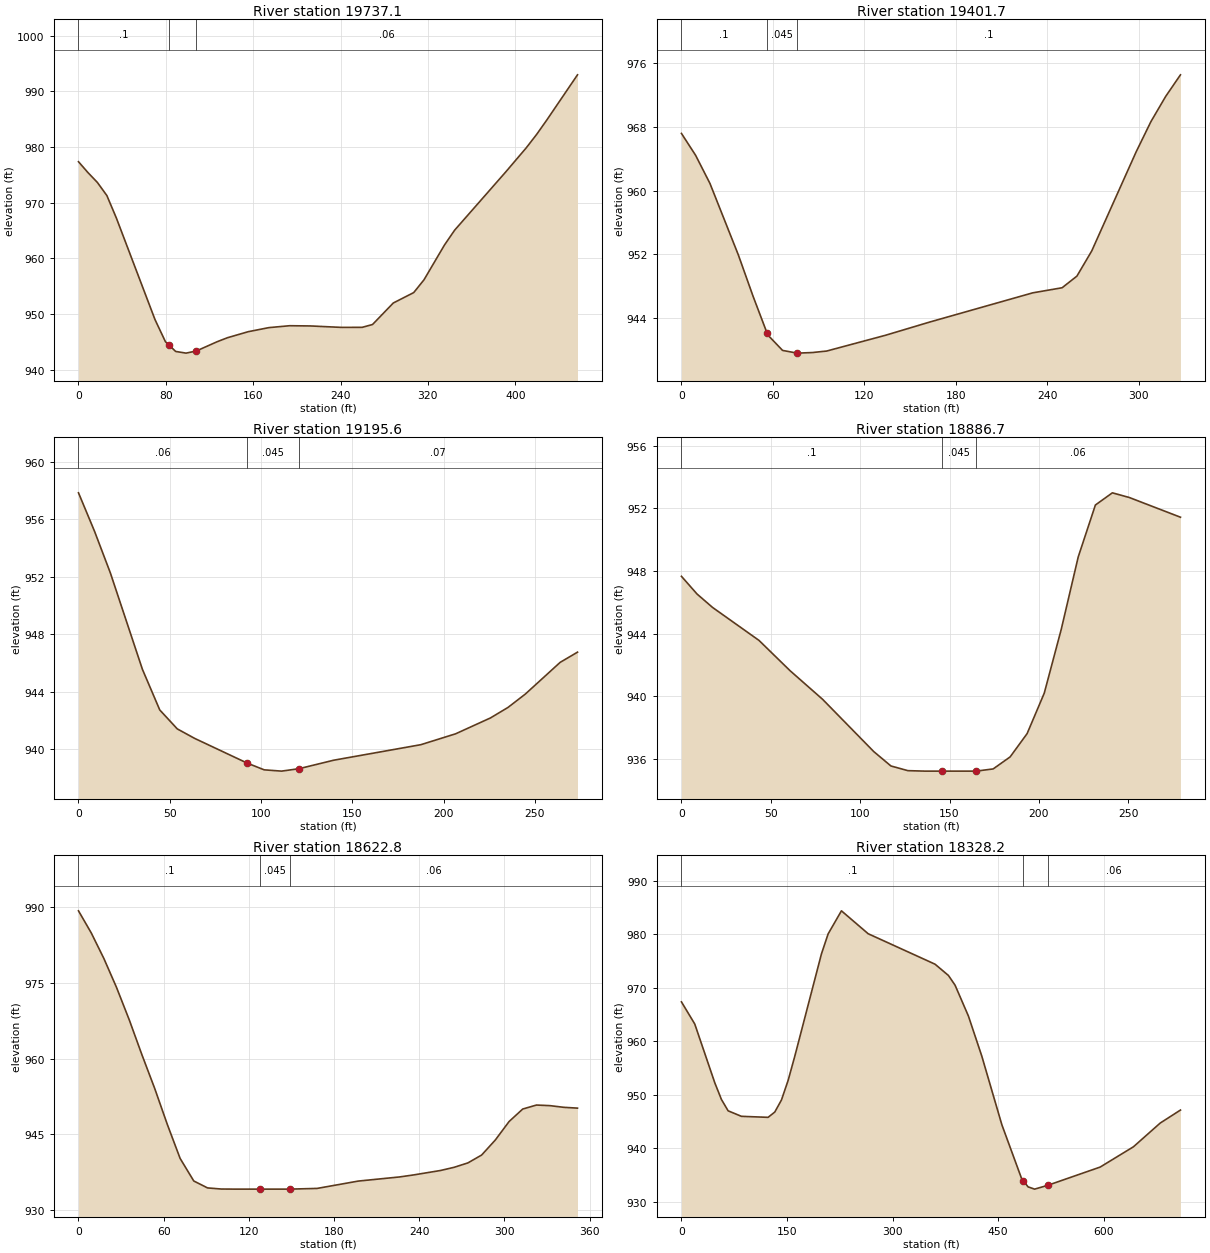
Type RM Length L Ch R = 1 ,19737.1 ,331.2,335.4,339.1
XS GIS Cut Line= 4
     1673248.643      732595.459     1673219.997      732648.844
     1673114.528      732850.667     1673019.476       732989.99
#Sta/Elev= 30
       0  977.35     8.7  975.39    17.3  973.63      26  971.27    34.6  967.28
    70.1  948.99    79.6  945.04    83.2  944.37      89  943.28    98.5  942.98
     108  943.37     127  945.03   136.5  945.75   155.5  946.83   174.4  947.56
   193.4   947.9   212.4  947.86   240.9   947.6   259.8  947.61   269.3  948.12
   288.3  951.98     307  953.85   316.4  956.14   335.2   962.4   344.5  965.06
   391.4  975.54   410.1  979.85   419.5  982.23   428.8  984.81     457  992.95
#Mann= 3 , 0 , 0
       0      .1       0    83.2    .045       0     108     .06       0
Bank Sta=83.2,108
XS Rating Curve= 0 ,0
Exp/Cntr=0.3,0.1

Type RM Length L Ch R = 1 ,19401.7 ,206.1,206.2,206.5
XS GIS Cut Line= 4
     1672956.976       732481.31     1672926.594      732503.011
     1672798.556      732672.282     1672763.834      732741.726
#Sta/Elev= 21
       0  967.16     9.3  964.41    18.7  960.88    37.3  951.92      47  946.71
      56  942.18    56.6  941.88    66.3  939.94    75.9   939.6    85.6  939.67
    95.2  939.86   133.8  941.84   162.8   943.5   230.3  947.16   249.6   947.8
   259.3  949.26     269  952.41   298.1  964.83   307.8  968.63   317.5   971.8
   327.2  974.51
#Mann= 3 , 0 , 0
       0      .1       0      56    .045       0    75.9      .1       0
Bank Sta=56,75.9
XS Rating Curve= 0 ,0
Exp/Cntr=0.3,0.1

Type RM Length L Ch R = 1 ,19195.6 ,310.1,308.9,297.3
XS GIS Cut Line= 3
     1672805.066      732351.101     1672774.684      732368.463
     1672629.285      732557.265
#Sta/Elev= 19
       0  957.84     8.8  955.16    17.5  952.25      35  945.56    44.5  942.73
    54.1  941.41    63.6  940.75    92.2  939.04   101.7  938.56   111.2  938.47
   120.8  938.64   139.8  939.23   187.5  940.31   206.6  941.07   225.6  942.17
   235.2   942.9   244.7  943.83   263.8  946.04   273.3  946.75
#Mann= 3 , 0 , 0
       0     .06       0    92.2    .045       0   120.8     .07       0
Bank Sta=92.2,120.8
XS Rating Curve= 0 ,0
Exp/Cntr=0.3,0.1

Type RM Length L Ch R = 1 ,18886.7 ,281,263.9,242.4
XS GIS Cut Line= 3
      1672544.65      732181.831     1672527.288      732249.105
     1672427.462      732433.567
#Sta/Elev= 22
       0  947.66     8.7  946.53    17.4  945.67    43.4  943.56    60.8  941.62
      79  939.79   107.6  936.45   117.2  935.53   126.7  935.23   136.2   935.2
   145.8   935.2   164.8   935.2   174.4  935.34   183.9  936.11   193.4   937.6
     203  940.19   212.5  944.27     222   948.9   231.6  952.22   241.1     953
   250.6   952.7   279.2  951.44
#Mann= 3 , 0 , 0
       0      .1       0   145.8    .045       0   164.8     .06       0
Bank Sta=145.8,164.8
XS Rating Curve= 0 ,0
Exp/Cntr=0.3,0.1

Type RM Length L Ch R = 1 ,18622.8 ,307.4,294.6,284.1
XS GIS Cut Line= 3
     1672303.764      732053.792     1672286.403      732123.237
     1672286.403      732403.185
#Sta/Elev= 30
       0  989.18       9  984.81    17.9  979.75    26.8  974.04    35.8  967.61
    44.7  960.73    53.7  954.08    62.6  946.96    71.6  940.26    81.2  935.81
    90.9  934.44   100.5  934.22   110.2   934.2     128   934.2   148.8   934.2
   168.1  934.34   197.1  935.79     226   936.6   235.7  936.99     255  937.88
   264.6  938.51   274.3  939.38     284  940.94   293.6   943.9   303.3  947.55
   312.9  950.02   322.6  950.81   332.2  950.69   341.9  950.36   351.5   950.2
#Mann= 3 , 0 , 0
       0      .1       0     128    .045       0   148.8     .06       0
Bank Sta=128,148.8
XS Rating Curve= 0 ,0
Exp/Cntr=0.3,0.1

Type RM Length L Ch R = 1 ,18328.2 ,138.5,121.2,103.2
XS GIS Cut Line= 5
     1671908.799      731802.056      1672062.46      731969.601
     1672006.455      732190.511     1672093.261       732322.89
     1672184.406      732351.101
#Sta/Elev= 30
       0  967.37    18.9  963.24    47.4  952.24    56.8  949.14    66.3  947.02
    85.2  945.99   123.1   945.8   132.6  946.79   142.1  949.05   151.6  952.72
     161   957.2   198.9  976.33   208.4  980.07   227.3  984.38   265.3   980.1
   360.3  974.41   379.3  972.31   388.8  970.48   407.8   964.7   426.8  957.21
   455.2  944.43   483.2  934.39   485.8  933.95   492.5  932.81   501.8  932.39
   520.4   933.1   594.9  936.51   642.2   940.3   680.3  944.74     709  947.16
#Mann= 3 , 0 , 0
       0      .1       0   485.8    .045       0   520.4     .06       0
Bank Sta=485.8,520.4
XS Rating Curve= 0 ,0
Exp/Cntr=0.3,0.1

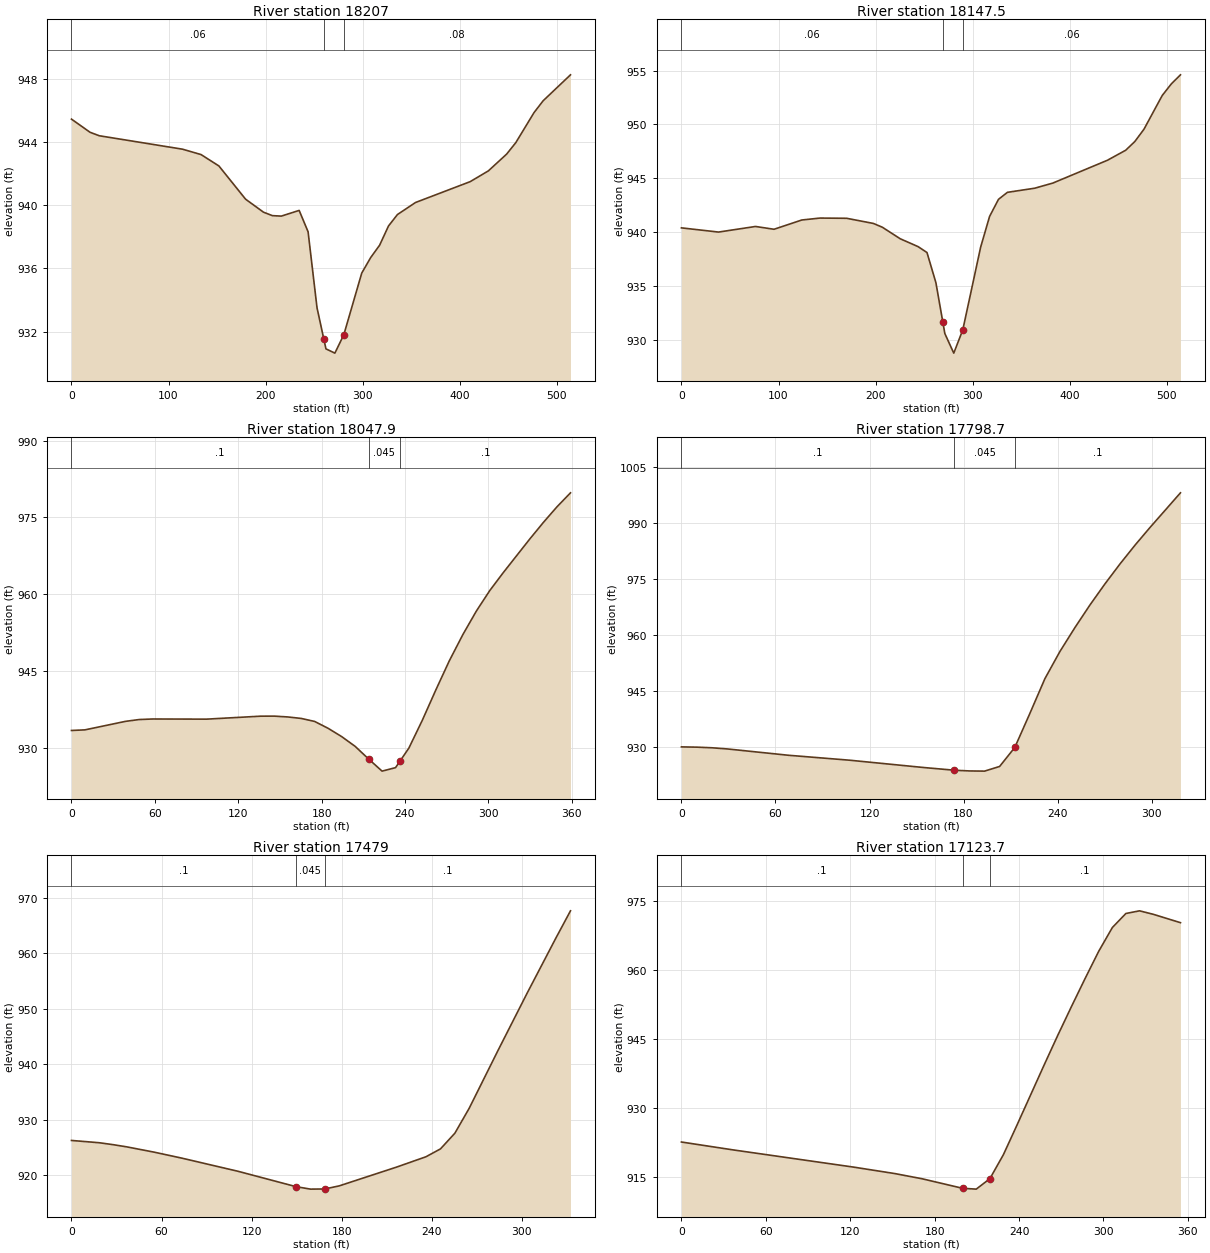
Type RM Length L Ch R = 1 ,18207   ,59.5,59.5,59.8
XS GIS Cut Line= 5
     1671683.104      732259.956     1671815.483      732277.317
     1671895.778      732296.848     1672021.646       732325.06
     1672186.577      732361.952
#Sta/Elev= 30
       0  945.44    19.1  944.61    28.6  944.39   114.4  943.54   133.5   943.2
   151.9  942.48   179.4  940.38   197.8  939.56     207  939.34   216.2  939.31
   234.6  939.67   243.8  938.32     253  933.52     260  931.54   262.2  930.92
   271.4  930.65   280.6  931.81   299.1  935.71   308.3  936.69   317.5  937.47
   326.7  938.69   335.9  939.41   354.5  940.17   410.9  941.49   429.6  942.17
   448.4  943.23   457.8  943.95   476.6  945.85     486   946.6   514.2  948.24
#Mann= 3 , 0 , 0
       0     .06       0     260    .045       0   280.6     .08       0
Bank Sta=260,280.6
XS Rating Curve= 0 ,0
Exp/Cntr=0.3,0.1

Type RM Length L Ch R = 1 ,18147.5 ,83.7,99.5,115.2
XS GIS Cut Line= 5
     1671654.893      732314.209     1671787.271       732331.57
     1671867.566      732351.101     1671993.434      732379.313
     1672158.365      732416.206
#Sta/Elev= 30
       0  940.39    38.2     940    76.3  940.52    95.4  940.26     124  941.12
   142.7   941.3   170.2  941.28   197.8   940.8     207  940.45   225.4  939.38
   243.8  938.65     253   938.1   262.2   935.3   269.3  931.66   271.4  930.58
   280.6  928.76   289.9  930.92   308.3   938.6   317.5  941.45   326.7  943.04
   335.9  943.69   363.9  944.07   382.7  944.55     439  946.67   457.8   947.6
   467.2  948.41   476.6  949.55   495.4  952.68   504.8  953.76   514.2   954.6
#Mann= 3 , 0 , 0
       0     .06       0   269.3    .045       0   289.9     .06       0
Bank Sta=269.3,289.9
XS Rating Curve= 0 ,0
Exp/Cntr=0.3,0.1

Type RM Length L Ch R = 1 ,18047.9 ,241.3,249.2,256.7
XS GIS Cut Line= 3
     1671687.445      732359.782     1671854.545      732411.865
     1671967.393      732557.265
#Sta/Elev= 30
       0  933.45     9.7  933.57    38.9  935.23    48.6  935.58    58.3  935.69
    97.2  935.66   136.1  936.24   145.9  936.25   155.6  936.09   165.3   935.8
     175  935.21   184.7  933.87   194.4  932.26   204.1  930.36   213.8  927.89
   223.5  925.52   233.2   926.2   236.6  927.55   242.8  930.02   252.5  935.46
   262.2  941.36   271.9  947.04   281.6  952.13   291.3  956.72     301  960.74
   310.6   964.2     330  970.87   339.7  974.07   349.4  977.09   359.1  979.81
#Mann= 3 , 0 , 0
       0      .1       0   213.8    .045       0   236.6      .1       0
Bank Sta=213.8,236.6
XS Rating Curve= 0 ,0
Exp/Cntr=0.3,0.1

Type RM Length L Ch R = 1 ,17798.7 ,317,319.8,321.3
XS GIS Cut Line= 3
     1671652.722      732416.206     1671650.552      732494.331
     1671726.507      732722.195
#Sta/Elev= 22
       0  929.93     9.8  929.86    19.5  929.69    29.3  929.38    68.4  927.68
     107  926.37     155  924.38   174.2  923.67   183.8  923.48   193.4  923.43
     203  924.68   212.7  929.79   222.3  938.89   231.9  948.23   241.5  955.53
   251.1  961.96   260.7  968.03   270.3   973.7   279.9  979.05   289.5  984.09
   299.1  988.85   318.4  998.08
#Mann= 3 , 0 , 0
       0      .1       0   174.2    .045       0   212.7      .1       0
Bank Sta=174.2,212.7
XS Rating Curve= 0 ,0
Exp/Cntr=0.3,0.1

Type RM Length L Ch R = 1 ,17479   ,343.6,355.3,365.7
XS GIS Cut Line= 3
     1671370.604      732476.969     1671359.754      732568.115
     1671414.007       732802.49
#Sta/Elev= 20
       0  926.25    18.4  925.84    27.5   925.5    36.7   925.1    55.1  924.14
    73.4  923.07     111  920.69   149.5  917.93   159.2  917.48   168.8  917.51
   178.4  918.07   216.9  921.48   236.1  923.31   245.8  924.73   255.4  927.56
     265  932.09   284.2  942.51   303.5  952.78   322.7  962.73   332.4  967.62
#Mann= 3 , 0 , 0
       0      .1       0   149.5    .045       0   168.8      .1       0
Bank Sta=149.5,168.8
XS Rating Curve= 0 ,0
Exp/Cntr=0.3,0.1

Type RM Length L Ch R = 1 ,17123.7 ,313.9,319.3,324.5
XS GIS Cut Line= 3
     1671081.976      732509.522     1671066.785      732611.518
     1671001.681      732854.574
#Sta/Elev= 20
       0  922.54    37.5  920.79   122.5  917.07   151.5  915.68   170.9  914.55
   199.9  912.46   209.6  912.28   219.3  914.56   228.9  919.78   238.6  926.25
     258  939.41   267.6   945.8   277.3  952.05     287  958.16   296.7   964.1
   306.4  969.27     316  972.32   325.7   972.9   335.4  972.15   354.8  970.32
#Mann= 3 , 0 , 0
       0      .1       0   199.9    .045       0   219.3      .1       0
Bank Sta=199.9,219.3
XS Rating Curve= 0 ,0
Exp/Cntr=0.3,0.1

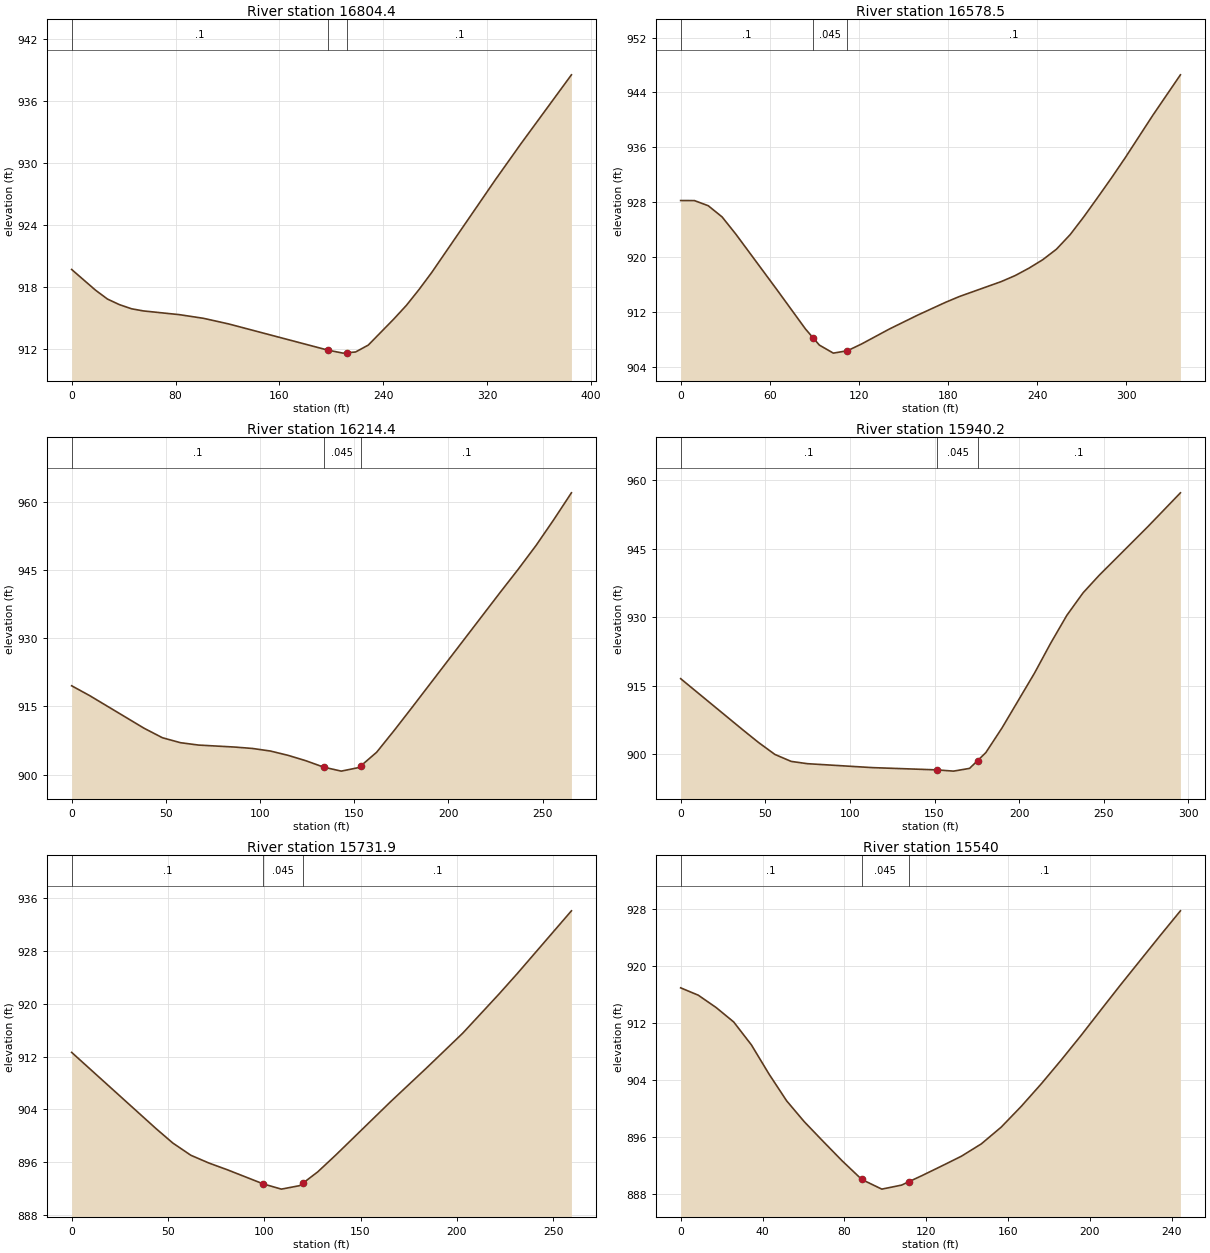
Type RM Length L Ch R = 1 ,16804.4 ,251,225.9,199.9
XS GIS Cut Line= 3
     1670875.813      732420.546     1670802.028       732489.99
     1670667.479      732739.556
#Sta/Elev= 21
       0  919.69    18.4  917.68    27.6  916.82    36.8  916.28    46.1  915.88
    55.3  915.67    82.9  915.31   101.3  914.96   120.9  914.41   197.3  911.87
   208.9  911.58   212.3  911.62   218.6  911.69   228.4  912.36     248  914.88
   257.8  916.22   267.5  917.75   277.3  919.41   326.2  928.38   345.7  931.84
   384.8  938.56
#Mann= 3 , 0 , 0
       0      .1       0   197.3    .045       0   212.3      .1       0
Bank Sta=197.3,212.3
XS Rating Curve= 0 ,0
Exp/Cntr=0.3,0.1

Type RM Length L Ch R = 1 ,16578.5 ,339.3,364.1,387.6
XS GIS Cut Line= 4
     1670480.847      732468.289      1670519.91      732520.372
     1670602.375       732635.39     1670624.077      732763.428
#Sta/Elev= 28
       0  928.25     9.3  928.24    18.6  927.49    27.9  925.86    37.2  923.34
    65.1  915.17      84  909.54      89  908.28    93.4  907.18   102.8  906.01
   112.3  906.36   121.7  907.33   140.6  909.53   159.4  911.53   178.3  913.41
   187.8  914.27   215.9  916.44   225.2  917.31   234.5  918.39   243.7  919.61
     253  921.15   262.3  923.29   271.6  925.92   280.8   928.7   290.1  931.55
   299.4  934.51   317.9  940.67   336.5  946.57
#Mann= 3 , 0 , 0
       0      .1       0      89    .045       0   112.3      .1       0
Bank Sta=89,112.3
XS Rating Curve= 0 ,0
Exp/Cntr=0.3,0.1

Type RM Length L Ch R = 1 ,16214.4 ,270.9,274.2,276.7
XS GIS Cut Line= 3
     1670313.747      732518.202     1670268.174      732591.987
     1670190.049      732752.577
#Sta/Elev= 23
       0  919.54     9.6  917.37    38.5  910.19    48.2  908.11    57.8  907.02
    67.4   906.5    86.7  906.06    96.1  905.75   105.5  905.19   114.9  904.24
   124.3  903.06   133.7  901.66   143.1  900.77   152.5  901.56   153.7  901.99
   161.9  904.92   171.3  909.76   180.7  914.78   227.7   940.2   237.1  945.19
   246.5  950.39   255.9  956.06   265.3  961.98
#Mann= 3 , 0 , 0
       0      .1       0   133.7    .045       0   153.7      .1       0
Bank Sta=133.7,153.7
XS Rating Curve= 0 ,0
Exp/Cntr=0.3,0.1

Type RM Length L Ch R = 1 ,15940.2 ,209.6,208.3,206.4
XS GIS Cut Line= 3
     1670101.073      732379.313     1670070.691      732414.035
     1669933.972      732622.369
#Sta/Elev= 20
       0  916.57    36.9  905.31    46.1  902.57    55.7  899.97    65.3  898.45
    74.9  897.95   113.2  897.09   151.6  896.59   161.2  896.32   170.7  896.92
   175.5  898.64   180.3  900.37   189.9  905.79   209.1   917.8   218.6  924.31
   228.2  930.45   237.8  935.38   247.4  939.25   276.2  949.92   295.3  957.27
#Mann= 3 , 0 , 0
       0      .1       0   151.6    .045       0   175.5      .1       0
Bank Sta=151.6,175.5
XS Rating Curve= 0 ,0
Exp/Cntr=0.3,0.1

Type RM Length L Ch R = 1 ,15731.9 ,190,191.9,193.6
XS GIS Cut Line= 3
      1669897.08      732288.167     1669871.038       732333.74
     1669769.042      732513.862
#Sta/Elev= 18
       0  912.65    43.7  901.13    52.5  898.92    61.9  897.06    71.3  895.88
    80.7  894.88    99.5  892.72   108.9  891.93   118.4  892.46   120.2  892.86
   127.8  894.55   137.2  897.11   165.4  905.12   184.2  910.27     203  915.54
   221.8  921.46   231.3  924.56   259.5   934.1
#Mann= 3 , 0 , 0
       0      .1       0    99.5    .045       0   120.2      .1       0
Bank Sta=99.5,120.2
XS Rating Curve= 0 ,0
Exp/Cntr=0.3,0.1

Type RM Length L Ch R = 1 ,15540   ,221.4,233.5,245.4
XS GIS Cut Line= 3
      1669745.17      732218.723     1669697.427      732268.636
     1669599.771      732414.035
#Sta/Elev= 29
       0  916.95     8.6  915.92    17.3  914.19    25.9  912.16    34.5  908.96
    43.2  904.82    51.8  901.06    60.4  898.13    69.1  895.52    78.8  892.66
    88.5  890.01    96.4  888.91    98.3  888.65     108  889.22   111.4  889.68
   117.7  890.52   127.4  891.88   137.2  893.28   146.9  895.01   156.6  897.36
   166.4  900.28   176.1  903.42   185.8  906.75   195.6  910.24   205.3  913.83
     215  917.39   224.8   920.9   234.5  924.37   244.2  927.78
#Mann= 3 , 0 , 0
       0      .1       0    88.5    .045       0   111.4      .1       0
Bank Sta=88.5,111.4
XS Rating Curve= 0 ,0
Exp/Cntr=0.3,0.1

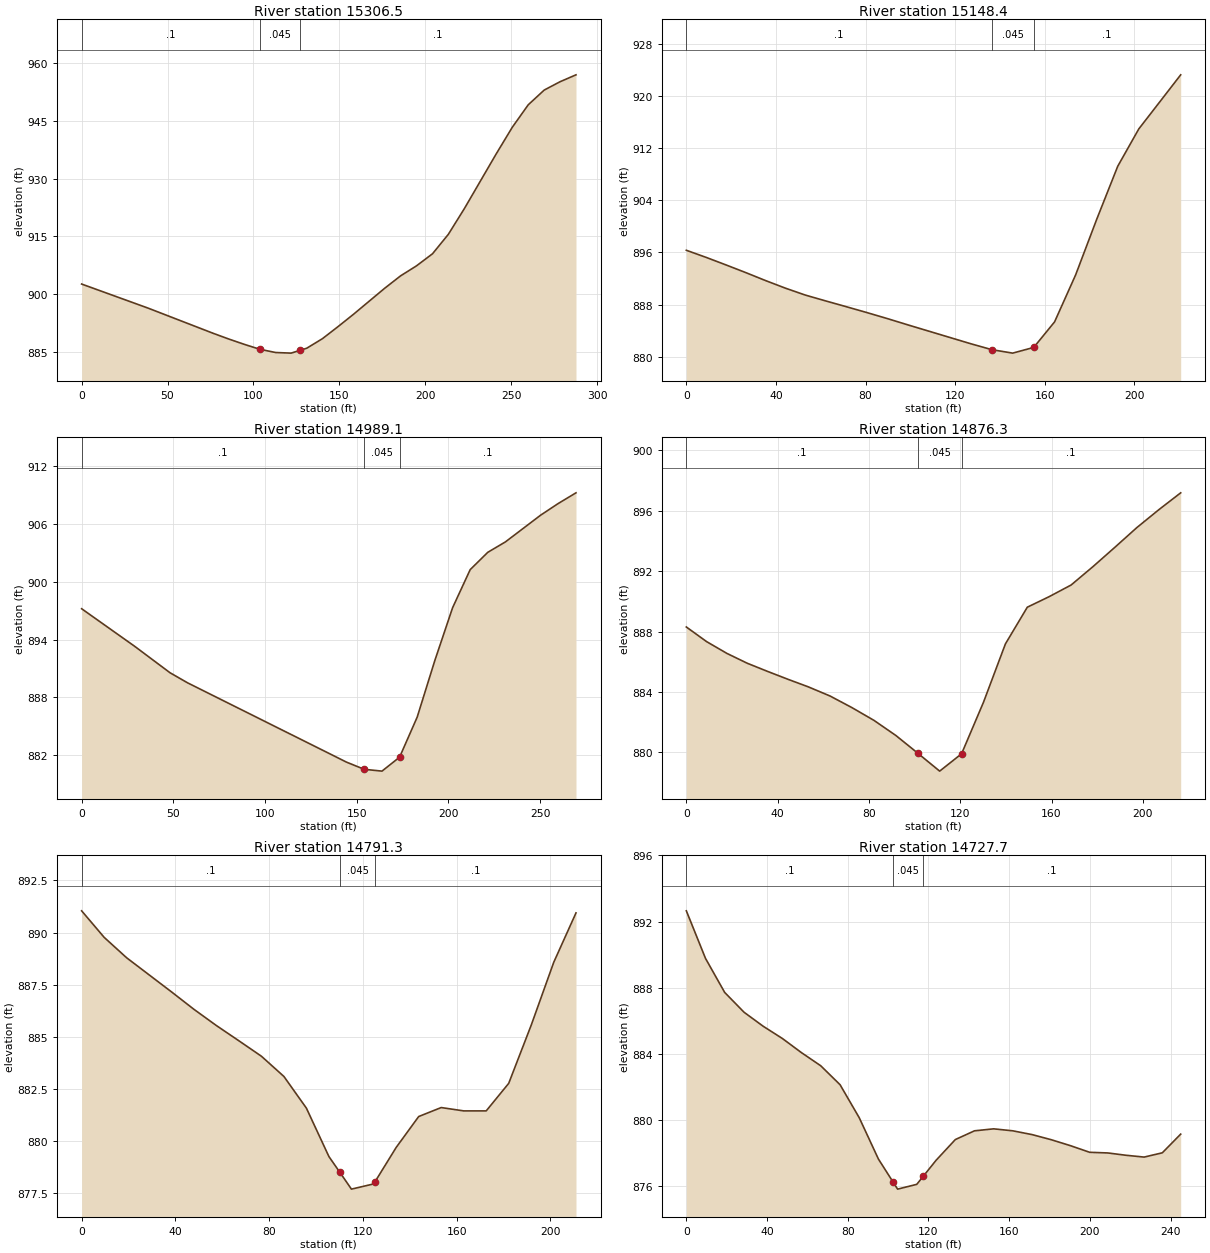
Type RM Length L Ch R = 1 ,15306.5 ,147.1,158.2,169.3
XS GIS Cut Line= 4
     1669610.622      732125.407     1669543.347      732131.917
     1669445.691       732179.66     1669335.014      732192.681
#Sta/Elev= 25
       0   902.6    38.6  896.36    76.6   889.8    85.7  888.31    94.8  886.92
   103.8  885.65   112.9  884.82   121.9  884.66     127  885.37     131  885.93
   140.1   888.4   149.1   891.5   158.2  894.74   176.3  901.48   185.6  904.72
   194.9  907.33   204.2  910.46   213.4   915.5   222.7  922.16   241.3  936.42
   250.6  943.29   259.9  949.14   269.2  952.97   278.4  955.13   287.7  956.93
#Mann= 3 , 0 , 0
       0      .1       0   103.8    .045       0     127      .1       0
Bank Sta=103.8,127
XS Rating Curve= 0 ,0
Exp/Cntr=0.3,0.1

Type RM Length L Ch R = 1 ,15148.4 ,159.2,159.2,159.2
XS GIS Cut Line= 4
     1669562.445      732049.018     1669494.736      732028.185
     1669391.872      732024.279     1669347.601      732039.904
#Sta/Elev= 27
       0  896.34     8.9  895.24    17.7  894.09    26.6   892.9    35.4  891.68
    44.3  890.51    53.1  889.46      62  888.58    70.8  887.73    80.2  886.81
    89.6  885.86    98.9  884.88   108.3  883.91   117.6  882.95     127  881.98
   136.4  881.07   138.5  880.95   145.7  880.54   153.5  881.27   155.1  881.42
   164.4  885.34   173.8  892.56   183.2  901.09   192.6  909.25     202  914.98
   211.3  919.11   220.7  923.29
#Mann= 3 , 0 , 0
       0      .1       0   136.4    .045       0   155.1      .1       0
Bank Sta=136.4,155.1
XS Rating Curve= 0 ,0
Exp/Cntr=0.3,0.1

Type RM Length L Ch R = 1 ,14989.1 ,112,112.9,113.6
XS GIS Cut Line= 3
      1669578.07      731900.581     1669486.924      731869.331
     1669313.747       731862.82
#Sta/Elev= 17
       0   897.2    28.9   893.3    48.2  890.55    57.8   889.5   144.5  881.26
   154.1  880.52   163.8  880.33   173.4  881.78     183  885.94   192.6  891.81
   202.3   897.3   211.9  901.26   221.5  903.06   231.1  904.14   250.4  906.93
     260  908.14   269.6  909.24
#Mann= 3 , 0 , 0
       0      .1       0   154.1    .045       0   173.4      .1       0
Bank Sta=154.1,173.4
XS Rating Curve= 0 ,0
Exp/Cntr=0.3,0.1

Type RM Length L Ch R = 1 ,14876.3 ,71.7,84.9,97.8
XS GIS Cut Line= 3
     1669533.799      731758.654     1669480.413      731758.654
     1669317.653      731746.935
#Sta/Elev= 26
       0   888.3     8.9  887.33    17.8  886.55    26.7   885.9    35.6  885.36
    44.5  884.84    53.4  884.34      63  883.73    72.6  882.96    82.2  882.12
    91.8  881.12   101.4  879.95   102.1  879.86     111  878.76   117.1  879.49
   120.6  879.91   130.2  883.32   139.8  887.18   149.4  889.61     159  890.31
   168.6  891.08   178.2   892.3   187.8  893.58   197.4  894.88     207  896.06
   216.6  897.18
#Mann= 3 , 0 , 0
       0      .1       0   101.4    .045       0   120.6      .1       0
Bank Sta=101.4,120.6
XS Rating Curve= 0 ,0
Exp/Cntr=0.3,0.1

Type RM Length L Ch R = 1 ,14791.3 ,63.5,63.7,63.5
XS GIS Cut Line= 2
     1669549.424      731748.237     1669381.455      731620.633
#Sta/Elev= 25
       0  891.04     9.6  889.77    19.2  888.79    28.8  887.97    38.4  887.15
    47.9  886.32    57.5  885.54    67.1  884.81    76.7  884.07    86.3   883.1
    95.9  881.58   105.5  879.26   110.2   878.5   115.1   877.7   124.6  877.95
   125.2  878.06   134.2   879.7   143.8  881.18   153.4  881.61     163  881.45
   172.6  881.45   182.2  882.77   191.8  885.56   201.4  888.57   210.9  890.94
#Mann= 3 , 0 , 0
       0      .1       0   110.2    .045       0   125.2      .1       0
Bank Sta=110.2,125.2
XS Rating Curve= 0 ,0
Exp/Cntr=0.3,0.1

Type RM Length L Ch R = 1 ,14727.7 ,155,128.3,101
XS GIS Cut Line= 3
     1669576.768      731689.643     1669417.588      731568.716
     1669372.543      731569.106
#Sta/Elev= 29
       0  892.65     9.5  889.77      19  887.71    28.6  886.51    38.1  885.66
    47.6  884.92    57.1  884.06    66.6  883.27    76.2  882.12    85.7  880.12
    95.2  877.62   102.5  876.22   104.7   875.8   114.2  876.09   117.5  876.59
   123.8  877.55   133.3   878.8   142.8  879.33   152.3  879.45   161.8  879.33
   171.4   879.1   180.9  878.79   190.4  878.43   199.9  878.03   208.9  877.99
   217.9  877.85   226.9  877.74   235.9     878     245  879.13
#Mann= 3 , 0 , 0
       0      .1       0   102.5    .045       0   117.5      .1       0
Bank Sta=102.5,117.5
XS Rating Curve= 0 ,0
Exp/Cntr=0.3,0.1