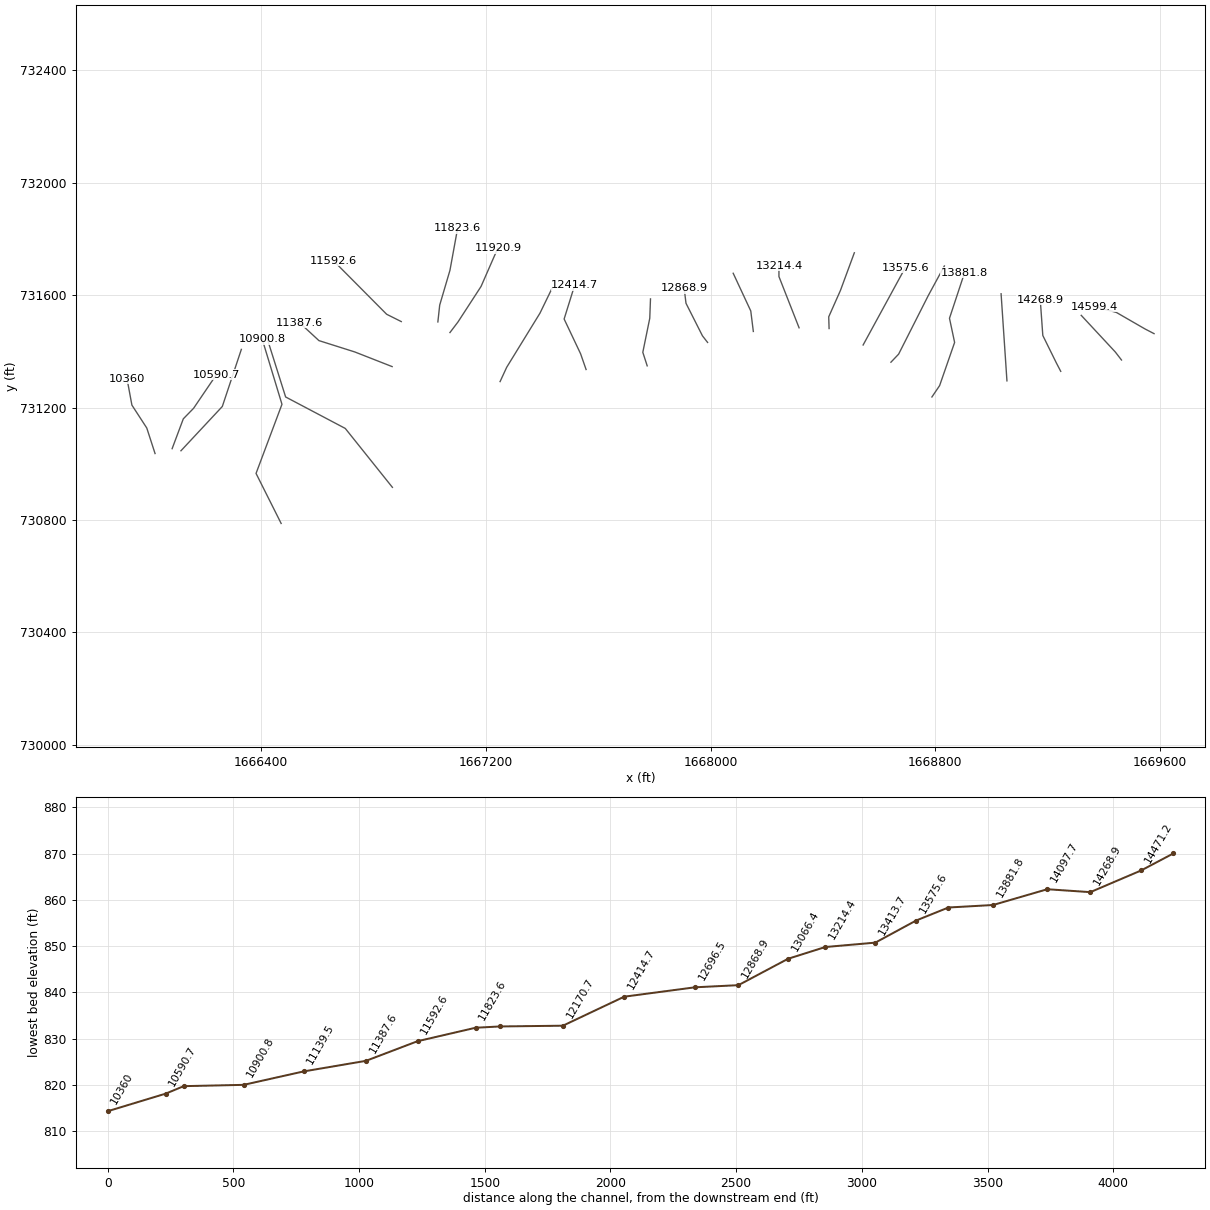
HEC-RAS study HARDINRUN.prj: HARDINRUN

--- HARDINRUN.g01 (geometry) --- (continued)

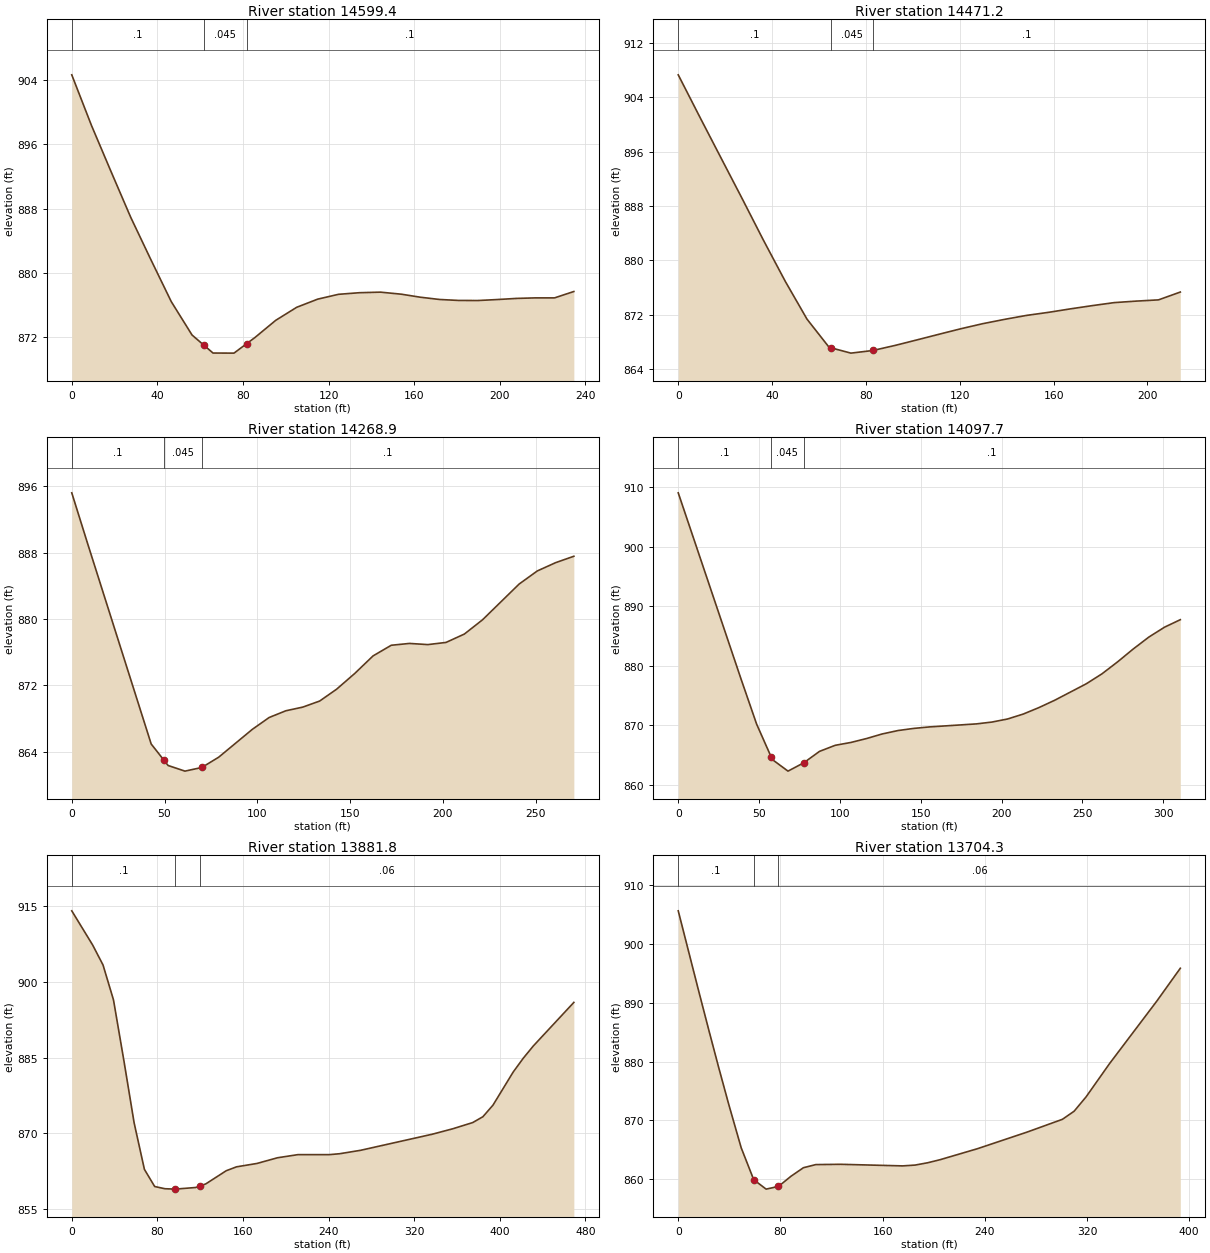
Type RM Length L Ch R = 1 ,14599.4 ,134.9,128.3,122
XS GIS Cut Line= 4
      1669578.07      731463.081     1669545.518      731480.008
     1669443.955      731538.601     1669366.033      731559.341
#Sta/Elev= 29
       0   904.6     9.2  898.32    18.4  892.56    27.5  886.94    36.7   881.8
    46.5  876.44    56.2   872.3   61.82871.0154      66  870.06    66.7  870.06
    75.8  870.05    81.7  871.22    85.6  871.99    95.3  874.12   105.1  875.74
   114.9  876.75   124.6  877.35   134.4  877.55   144.2  877.62   153.9  877.37
   162.9  876.99   171.9  876.71   180.8  876.59   189.8  876.58   198.7   876.7
   207.7  876.84   216.7  876.91   225.6  876.91   234.6   877.7
#Mann= 3 , 0 , 0
       0      .1       0   61.82    .045       0    81.7      .1       0
Bank Sta=61.82,81.7
XS Rating Curve= 0 ,0
Exp/Cntr=0.3,0.1

Type RM Length L Ch R = 1 ,14471.2 ,208.5,202.3,195.4
XS GIS Cut Line= 3
     1669462.184      731369.331     1669440.049      731397.976
     1669318.955      731528.185
#Sta/Elev= 26
       0  907.29       9  901.22    18.1  895.16    27.2  889.12    36.2  883.05
    45.6  876.94    54.9  871.36    64.3  867.23    64.9  867.17    73.6  866.37
    79.9  866.63      83  866.76    92.4   867.5   101.7  868.31   111.1  869.14
   120.4  869.95   129.8   870.7   139.2  871.34   148.5  871.92   157.9  872.37
   167.2  872.88   176.6  873.36   185.9   873.8   195.3  874.02   204.7   874.2
     214  875.35
#Mann= 3 , 0 , 0
       0      .1       0    64.9    .045       0      83      .1       0
Bank Sta=64.9,83
XS Rating Curve= 0 ,0
Exp/Cntr=0.3,0.1

Type RM Length L Ch R = 1 ,14268.9 ,180.1,171.1,162
XS GIS Cut Line= 4
     1669246.038      731328.966     1669230.413      731358.914
     1669182.236       731456.57     1669173.122      731584.174
#Sta/Elev= 26
       0   895.2     8.4  889.19    42.8  864.95    49.7  862.99    51.9  862.36
      61  861.68    70.1  862.12    79.2  863.36    97.3  866.71   106.4  868.14
   115.4  868.95   124.5  869.39   133.6  870.12   142.7  871.54   152.5  873.44
   162.4  875.56   172.2  876.84     182  877.06   191.9  876.92   201.7  877.18
   211.6  878.19   221.4  879.91   241.1  884.21   250.9  885.79   260.8  886.79
   270.6  887.56
#Mann= 3 , 0 , 0
       0      .1       0    49.7    .045       0    70.1      .1       0
Bank Sta=49.7,70.1
XS Rating Curve= 0 ,0
Exp/Cntr=0.3,0.1

Type RM Length L Ch R = 1 ,14097.7 ,225.3,215.9,205.7
XS GIS Cut Line= 2
     1669054.632      731295.112     1669033.799      731605.008
#Sta/Elev= 28
       0   909.1    38.8  877.84    48.5  870.21    57.4  864.75    58.2  864.26
    67.9  862.31    77.6   863.7    87.4  865.63    97.1  866.65   106.8  867.13
   116.5  867.79   126.2  868.56   135.9  869.13   145.6  869.49   155.3  869.74
   184.4  870.25   194.1  870.56   203.8  871.08   213.5  871.91   223.2     873
     233  874.24   252.4  876.99   262.1  878.66   271.8  880.68   281.5  882.85
   291.2  884.86   300.9  886.52   310.6  887.77
#Mann= 3 , 0 , 0
       0      .1       0    57.4    .045       0    77.6      .1       0
Bank Sta=57.4,77.6
XS Rating Curve= 0 ,0
Exp/Cntr=0.3,0.1

Type RM Length L Ch R = 1 ,13881.8 ,179.7,177.5,175.6
XS GIS Cut Line= 5
     1668787.705       731237.82     1668815.049      731278.185
     1668868.434      731431.831     1668850.205      731517.768
     1668903.591      731679.226
#Sta/Elev= 30
       0  914.09    19.5  907.32    29.2  903.36      39  896.42    48.8  884.28
    58.3  872.03    67.9  862.82    77.5  859.42      87  858.98    96.6   858.9
   115.7  859.22   119.6  859.51   125.3  859.94   144.4  862.55     154  863.32
   173.1  863.99   192.3  865.12   211.4  865.74   240.7  865.74   250.4  865.92
     270   866.6     337  869.79     356  870.86   374.8   872.1   384.3  873.26
   393.7  875.55   412.6  882.12   422.1  884.88   431.5  887.31   469.3  895.93
#Mann= 3 , 0 , 0
       0      .1       0    96.6    .045       0   119.6     .06       0
Bank Sta=96.6,119.6
XS Rating Curve= 0 ,0
Exp/Cntr=0.3,0.1

Type RM Length L Ch R = 1 ,13704.3 ,129.4,128.7,127.4
XS GIS Cut Line= 4
     1668641.872      731361.518     1668669.216      731390.164
     1668774.684      731598.497     1668831.976      731703.966
#Sta/Elev= 25
       0  905.56    15.8  892.14    23.8  885.45    31.7  878.97    39.6  872.69
    49.3  865.37    59.1  859.96    68.8  858.36    78.5  858.82    88.2  860.53
      98  861.99   107.7  862.52   127.2  862.57   175.8   862.3   185.5  862.44
   195.3  862.83     205  863.35   234.2  865.21   273.1  868.03   300.8   870.2
     310  871.58   319.3     874   337.7  879.65   374.7  890.25   393.1  895.82
#Mann= 3 , 0 , 0
       0      .1       0    59.1    .045       0    78.5     .06       0
Bank Sta=59.1,78.5
XS Rating Curve= 0 ,0
Exp/Cntr=0.3,0.1

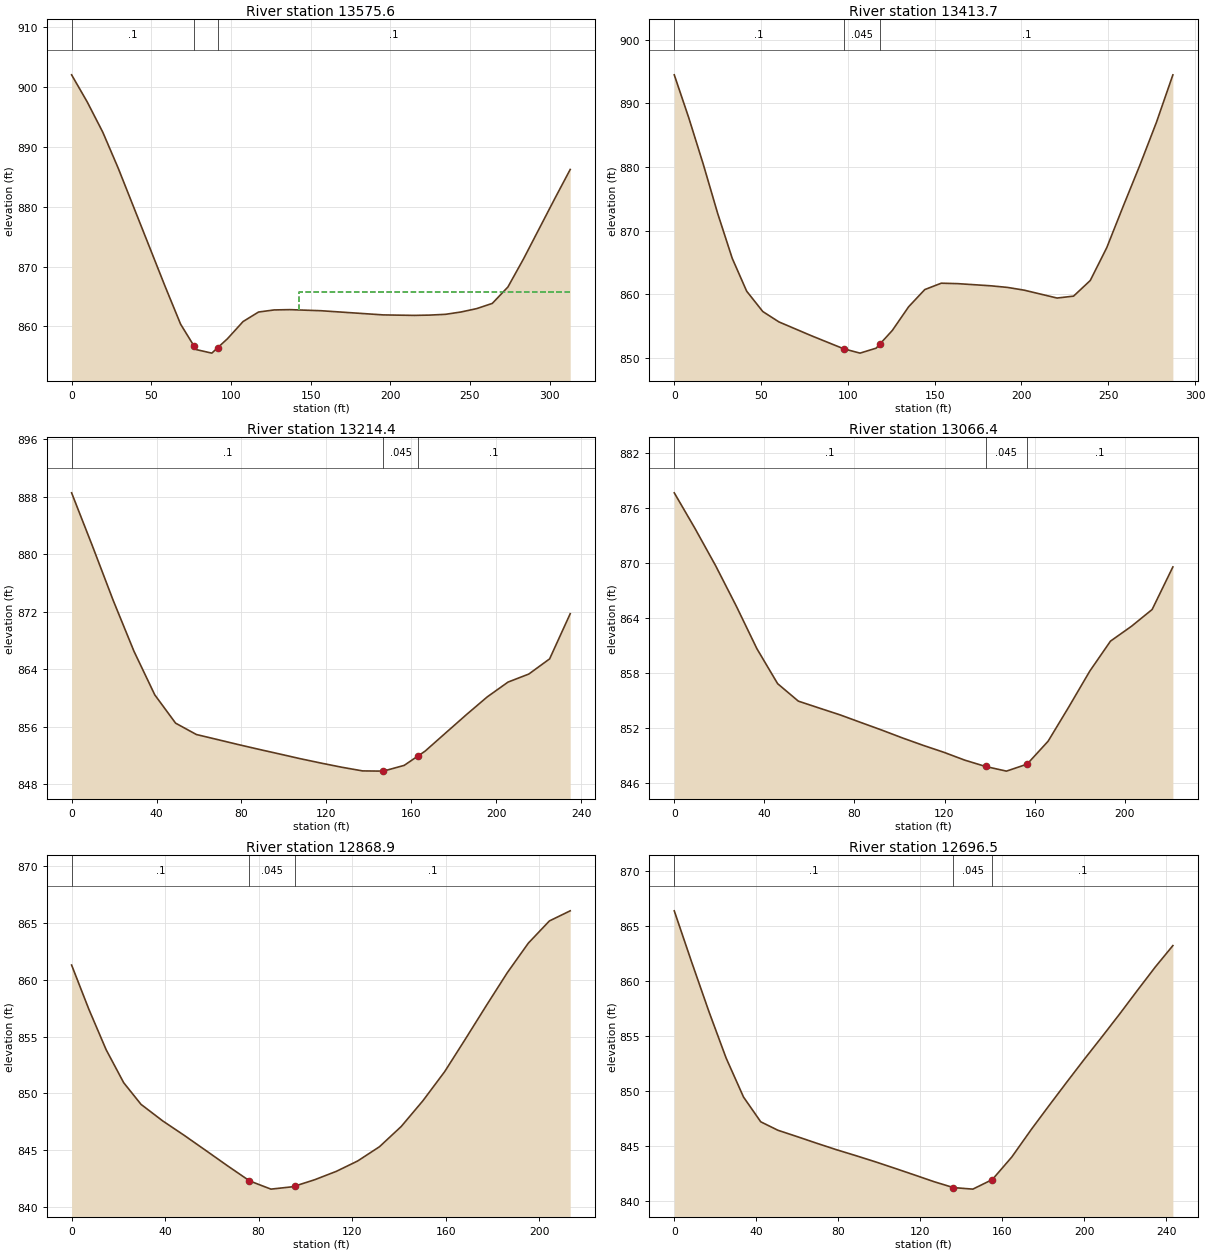
Type RM Length L Ch R = 1 ,13575.6 ,159.9,161.9,163.7
XS GIS Cut Line= 2
     1668542.913      731422.716     1668692.653      731697.456
#Sta/Elev= 27
       0     902     9.8  897.48    19.6  892.41    29.3  886.39    58.7  866.67
    68.4  860.38    76.7  856.78    78.2  856.13      88  855.54    91.7  856.45
    97.8  857.94   107.6  860.81   117.3   862.4   127.1  862.75   136.9   862.8
   156.4  862.62   195.6  861.92   215.1  861.84   224.9  861.89   234.7  862.02
   244.4  862.41   254.2  862.97     264  863.84   273.8  866.58   283.6  871.27
   303.1  881.28   312.9   886.2
#Mann= 3 , 0 , 0
       0      .1       0    76.7    .045       0    91.7      .1       0
#XS Ineff= 2 , 0
                           142.6          865.77
Permanent Ineff=
       F       F
Bank Sta=76.7,91.7
XS Rating Curve= 0 ,0
Exp/Cntr=0.3,0.1

Type RM Length L Ch R = 1 ,13413.7 ,181.1,199.3,217.4
XS GIS Cut Line= 4
      1668421.82       731481.31     1668420.518      731522.976
     1668462.184      731616.726     1668511.663      731750.841
#Sta/Elev= 29
       0  894.47     8.3  887.77    16.7  880.44      25  872.71    33.4  865.65
    41.7   860.5      51   857.3    60.3  855.67      79   853.5    97.6  851.45
     107  850.77   116.3  851.55   118.5  852.21   125.6  854.33     135  858.05
   144.3  860.75   153.8  861.75   163.3  861.68   182.4  861.34   191.9  861.09
   201.5  860.66   220.5  859.42     230  859.72   239.6  862.17   249.1  867.32
   258.6  873.84   268.2  880.29   277.7  886.99   287.2  894.46
#Mann= 3 , 0 , 0
       0      .1       0    97.6    .045       0   118.5      .1       0
Bank Sta=97.6,118.5
XS Rating Curve= 0 ,0
Exp/Cntr=0.3,0.1

Type RM Length L Ch R = 1 ,13214.4 ,146.7,147.9,148.8
XS GIS Cut Line= 4
     1668315.049      731483.914     1668300.726      731520.372
     1668243.434      731666.206     1668243.434      731705.268
#Sta/Elev= 27
       0  888.52     9.8  881.14    19.6  873.56    29.4  866.48    39.2  860.42
      49  856.49    58.8  854.91    68.6  854.22    78.3  853.53    88.1  852.86
    97.9  852.21   107.7  851.55   117.5  850.94   127.3  850.36   137.1  849.85
   146.9  849.82   148.2  849.93   156.7  850.62   163.2  851.93   166.5  852.59
   176.3  855.15   186.1   857.7   195.8  860.14   205.6   862.2   215.4  863.32
   225.2  865.43   234.9  871.71
#Mann= 3 , 0 , 0
       0      .1       0   146.9    .045       0   163.2      .1       0
Bank Sta=146.9,163.2
XS Rating Curve= 0 ,0
Exp/Cntr=0.3,0.1

Type RM Length L Ch R = 1 ,13066.4 ,196.7,197.5,198.1
XS GIS Cut Line= 3
     1668152.288      731470.893     1668143.174       731543.81
     1668080.674      731677.924
#Sta/Elev= 27
       0   877.7     9.2  873.81    18.4  869.72    27.6  865.29    36.7  860.66
    45.9  856.84    55.1  854.93    64.3  854.18    73.5  853.44    82.7  852.61
      92  851.78   101.2  850.92   110.5   850.1   119.7  849.34     129  848.48
   138.2  847.79   140.2  847.68   147.5  847.28   155.2  847.92   156.7  848.05
     166  850.55   175.2   854.3   184.5  858.21   193.7  861.49     203  863.11
   212.2  864.95   221.4   869.6
#Mann= 3 , 0 , 0
       0      .1       0   138.2    .045       0   156.7      .1       0
Bank Sta=138.2,156.7
XS Rating Curve= 0 ,0
Exp/Cntr=0.3,0.1

Type RM Length L Ch R = 1 ,12868.9 ,187.5,172.4,157.2
XS GIS Cut Line= 4
     1667989.528      731431.831     1667971.299      731455.268
     1667912.705      731571.154     1667906.195      731624.539
#Sta/Elev= 27
       0   861.3     7.4   857.4    14.8  853.84    22.3  850.94    29.7  849.04
      39  847.58    48.2  846.31    57.5  844.97    66.8  843.62    76.1  842.31
    80.7  841.94    85.3  841.58    94.6  841.79    95.7  841.86   103.9   842.4
   113.2  843.14   122.4  844.06   131.7  845.31     141  847.09   150.3  849.36
   159.6  851.92   168.5   854.8   177.5  857.76   186.4  860.63   195.4  863.23
   204.4  865.18   213.3  866.07
#Mann= 3 , 0 , 0
       0      .1       0    76.1    .045       0    95.7      .1       0
Bank Sta=76.1,95.7
XS Rating Curve= 0 ,0
Exp/Cntr=0.3,0.1

Type RM Length L Ch R = 1 ,12696.5 ,267.1,281.8,296.2
XS GIS Cut Line= 4
     1667774.684      731348.497     1667759.059      731396.674
     1667783.799      731517.768     1667786.403      731586.779
#Sta/Elev= 29
       0  866.42     8.4  861.81    16.9  857.27    25.3  853.04    33.8  849.49
    42.2  847.24    50.6  846.47    60.2  845.88    69.7  845.28    79.2   844.7
    88.7  844.16    98.2   843.6   107.7  843.01   117.2  842.41   126.7   841.8
   136.2  841.26   140.2   841.2   145.7  841.12   155.2  841.99   164.7  844.04
   174.2  846.54   182.9  848.72   191.5  850.84   200.1  852.93   208.8  854.99
   217.4  857.06     226  859.19   234.7  861.31   243.3  863.26
#Mann= 3 , 0 , 0
       0      .1       0   136.2    .045       0   155.2      .1       0
Bank Sta=136.2,155.2
XS Rating Curve= 0 ,0
Exp/Cntr=0.3,0.1

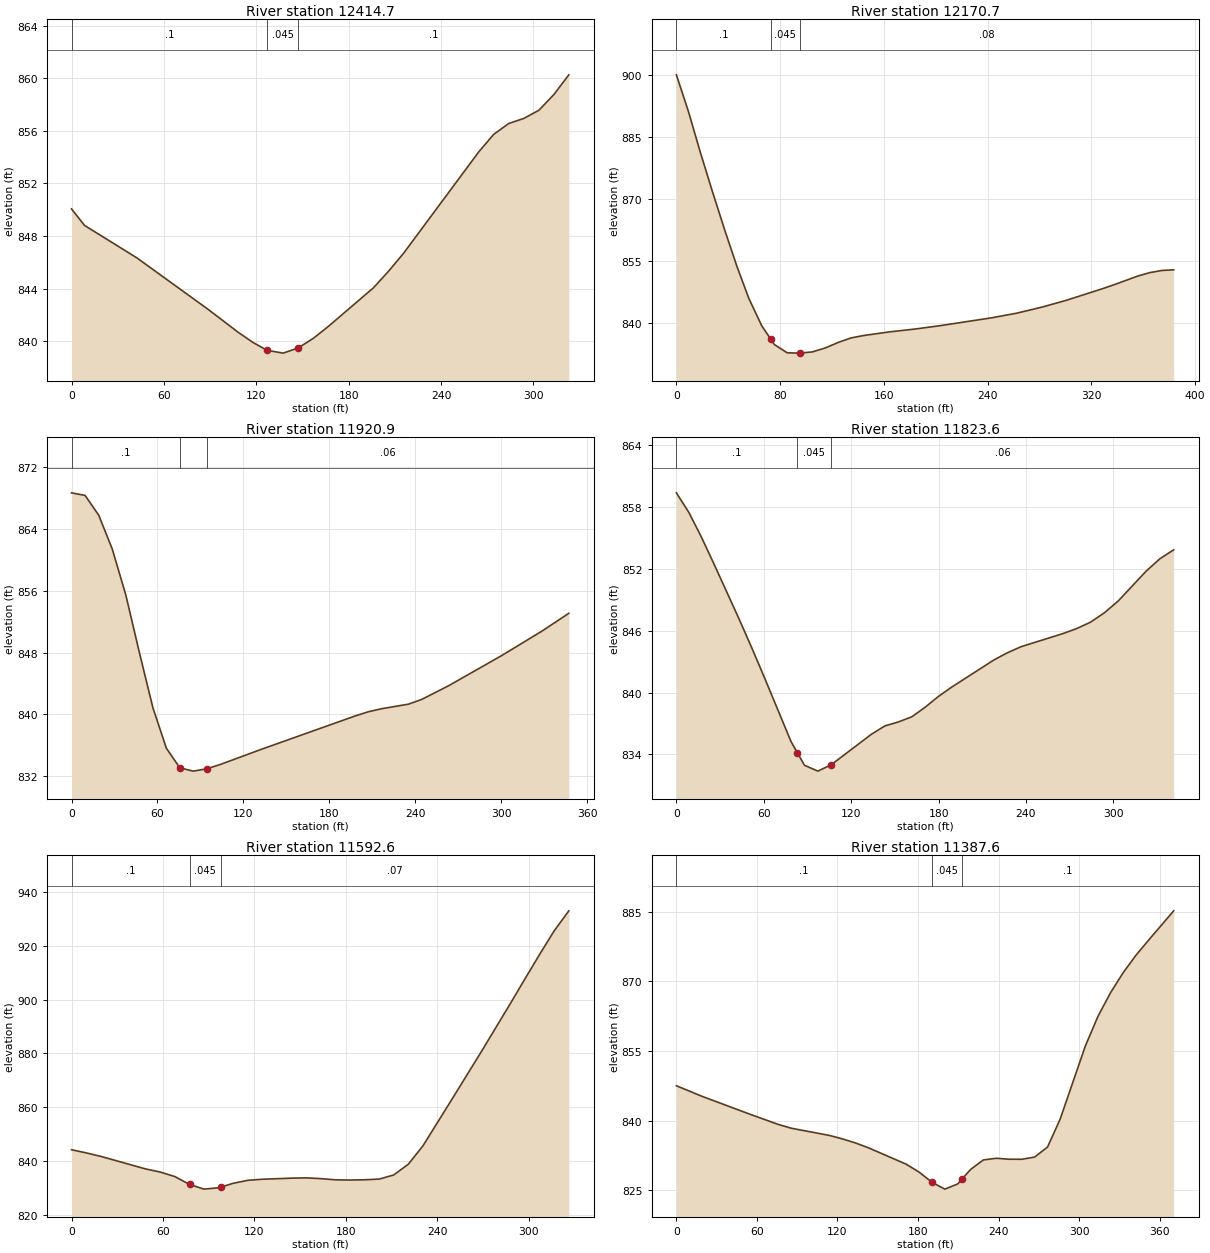
Type RM Length L Ch R = 1 ,12414.7 ,266.3,244,220.5
XS GIS Cut Line= 4
     1667557.236      731335.476     1667537.705      731391.466
     1667479.111      731515.164     1667516.872      731636.258
#Sta/Elev= 21
       0  850.06     8.5   848.8    42.4  846.34    88.6  842.43   108.2  840.68
     118  839.89   127.1   839.3   137.5  839.09   147.3  839.49   157.1  840.22
   166.8  841.12   196.2  844.07   205.9  845.32   215.7  846.69   264.5   854.4
   274.2  855.73     284  856.56   293.7  856.94   303.5  857.56   313.3  858.76
     323  860.26
#Mann= 3 , 0 , 0
       0      .1       0   127.1    .045       0   147.3      .1       0
Bank Sta=127.1,147.3
XS Rating Curve= 0 ,0
Exp/Cntr=0.3,0.1

Type RM Length L Ch R = 1 ,12170.7 ,249.7,249.8,249.6
XS GIS Cut Line= 4
     1667251.247      731292.508     1667274.684      731343.289
     1667393.174      731535.997     1667437.445      731627.143
#Sta/Elev= 30
       0  899.94     9.3  891.08    18.6   881.1      28  871.58    37.3  862.48
    46.6  853.81    55.9  845.99    65.8  839.43    72.8  836.18    75.6  834.88
    85.4   832.9    95.3  832.82   105.1  833.13   114.9  834.08   124.8   835.4
   134.6  836.48   144.4  837.07   164.1  837.93   183.8  838.62   203.5  839.45
   242.8  841.32   262.5  842.46   282.2  843.94   300.6  845.55   328.2  848.32
   337.4   849.3   355.8  851.41   365.1  852.24   374.3  852.75   383.5  852.91
#Mann= 3 , 0 , 0
       0      .1       0    72.8    .045       0    95.3     .08       0
Bank Sta=72.8,95.3
XS Rating Curve= 0 ,0
Exp/Cntr=0.3,0.1

Type RM Length L Ch R = 1 ,11920.9 ,90.6,97.3,103.7
XS GIS Cut Line= 4
     1667072.861      731466.987     1667101.507      731504.747
     1667183.538      731631.049     1667243.434      731767.768
#Sta/Elev= 22
       0  868.66     9.5  868.32      19  865.76    28.4  861.41    37.9  855.46
    47.4  847.99    56.8  840.88    66.2  835.64    75.6  833.09      85  832.66
    94.5  832.96   103.9  833.52   132.1  835.45     198  839.79   207.3  840.34
   216.7  840.74   235.3  841.32   244.6  841.94   263.3   843.7   300.6  847.63
   328.6  850.78   347.3  853.08
#Mann= 3 , 0 , 0
       0      .1       0    75.6    .045       0    94.5     .06       0
Bank Sta=75.6,94.5
XS Rating Curve= 0 ,0
Exp/Cntr=0.3,0.1

Type RM Length L Ch R = 1 ,11823.6 ,206.1,231,254.8
XS GIS Cut Line= 4
     1667029.893      731504.747     1667036.403      731564.643
     1667072.861      731688.341     1667100.205      731838.081
#Sta/Elev= 30
       0  859.38     8.6  857.47    17.2  855.08    25.8  852.48      43  847.15
    51.6  844.39    60.2  841.54    78.7  835.25    83.1  834.15    87.9  832.95
    97.1  832.38   106.3     833   133.9  835.96   143.2  836.77   152.4  837.15
   161.6  837.65   170.8  838.58     180  839.64   189.2  840.55   217.8  843.15
   227.3  843.87   236.8  844.46   265.3  845.72   274.8  846.21   284.3  846.83
   293.9  847.75   303.4   848.9   322.4  851.77   331.9  852.98   341.4  853.85
#Mann= 3 , 0 , 0
       0      .1       0    83.1    .045       0   106.3     .06       0
Bank Sta=83.1,106.3
XS Rating Curve= 0 ,0
Exp/Cntr=0.3,0.1

Type RM Length L Ch R = 1 ,11592.6 ,193.7,205,216.1
XS GIS Cut Line= 3
     1666899.684      731506.049     1666847.601      731532.091
     1666658.799      731722.195
#Sta/Elev= 30
       0  844.14     9.7  842.96    19.4  841.64    48.5     837    58.2  835.83
    67.8  834.14    77.4  831.22    86.9  829.47    96.5  829.97    98.1  830.25
   106.1  831.65   115.6  832.75   125.2  833.15   144.4  833.56   153.9  833.66
   163.5  833.38   173.1  832.94   182.6  832.85   192.2  832.95   201.8  833.21
   211.3  834.73   220.9  838.74   230.5  845.58   249.6     863   268.8  880.66
   287.9  898.64   297.4  907.75     307  916.84   316.6  925.66   326.2  933.11
#Mann= 3 , 0 , 0
       0      .1       0    77.4    .045       0    98.1     .07       0
Bank Sta=77.4,98.1
XS Rating Curve= 0 ,0
Exp/Cntr=0.3,0.1

Type RM Length L Ch R = 1 ,11387.6 ,252.4,248.1,243.5
XS GIS Cut Line= 4
     1666867.132      731345.893      1666734.32      731397.976
     1666606.716      731438.341     1666537.705      731502.143
#Sta/Elev= 30
       0   847.5      19  845.23    57.1  841.12    76.1  839.15    85.6  838.35
   114.1  836.79   123.6  836.06   133.2   835.2   142.7  834.18   171.3  830.59
   180.9  828.88   190.5  826.69     200  825.23   209.6  826.35   212.8  827.39
   219.1  829.45   228.7  831.52   238.3  831.88   247.8  831.67   257.4  831.66
   266.9  832.14   276.5  834.29   285.9   840.3   304.7  856.08   314.1  862.46
   323.5  867.57   332.9  871.87   342.3  875.58   351.7  878.83   370.5  885.18
#Mann= 3 , 0 , 0
       0      .1       0   190.5    .045       0   212.8      .1       0
Bank Sta=190.5,212.8
XS Rating Curve= 0 ,0
Exp/Cntr=0.3,0.1

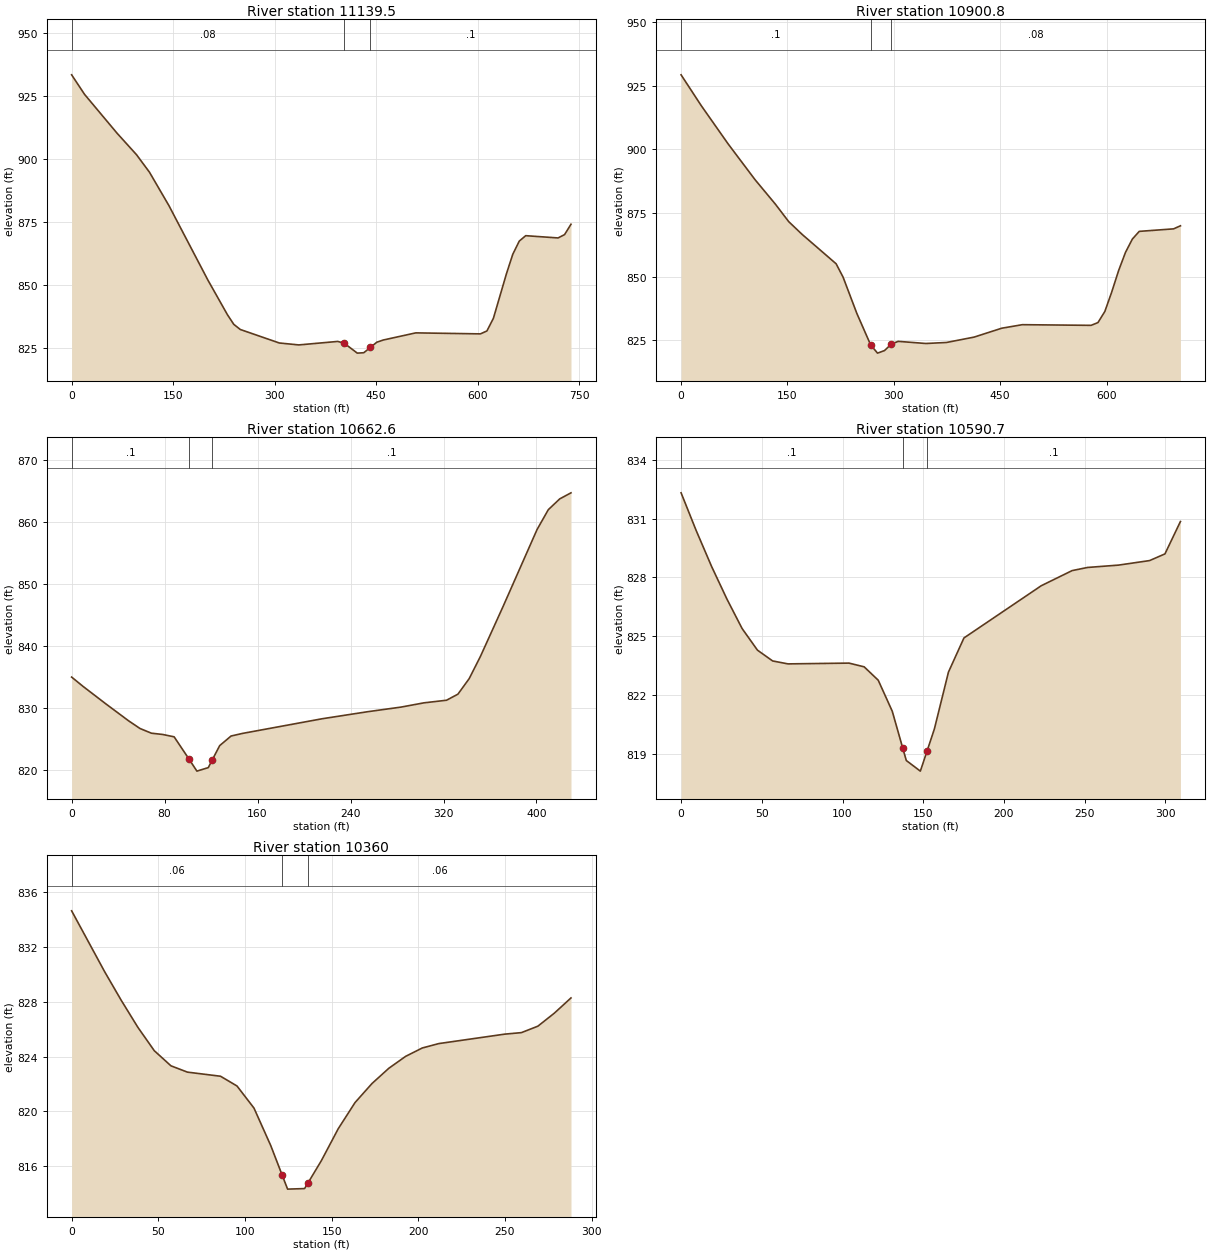
Type RM Length L Ch R = 1 ,11139.5 ,271.8,238.7,204.5
XS GIS Cut Line= 4
      1666868.13      730916.256     1666700.466      731125.841
     1666488.226       731237.82     1666419.216       731456.57
#Sta/Elev= 30
       0  933.55    19.2  925.75    67.1  910.35    95.9  901.79     115  894.84
   143.8  881.54   201.3  851.97   230.1  838.24   239.6  834.36   249.2  832.33
   306.8  826.97   335.6   826.2   393.2  827.59   402.8  826.85     422  822.94
   431.6   823.1   441.2  825.18   450.8  827.27   460.4  828.15   508.4  830.99
   603.9  830.59   613.5  831.75   623.1   836.8   642.2  854.36   651.7  862.23
   661.3  867.46   670.8  869.62   718.6  868.72   728.2  870.04   737.7  874.16
#Mann= 3 , 0 , 0
       0     .08       0   402.8    .045       0   441.2      .1       0
Bank Sta=402.8,441.2
XS Rating Curve= 0 ,0
Exp/Cntr=0.3,0.1

Type RM Length L Ch R = 1 ,10900.8 ,246.9,238.1,229.3
XS GIS Cut Line= 4
     1666472.297      730787.784     1666382.968      730965.814
     1666475.205      731211.779     1666404.893      731443.549
#Sta/Elev= 30
       0  929.24    28.4  917.16    66.4  902.11   104.3  888.09   132.8  878.55
   151.8  871.62   170.7  866.62   218.6   855.1   228.4  849.87   247.8  835.64
   267.3  823.26     277  820.04   286.8  821.04   296.5  823.61   306.2  824.66
   345.1  823.82   374.3  824.22   413.2  826.33   452.2  829.82   481.2   831.2
   578.1  830.94   587.8  832.03   597.5  836.38   607.2  844.02   616.9  852.41
   626.6  859.57   636.3  864.79     646  867.81   694.4   868.8   704.1     870
#Mann= 3 , 0 , 0
       0      .1       0   267.3    .045       0   296.5     .08       0
Bank Sta=267.3,296.5
XS Rating Curve= 0 ,0
Exp/Cntr=0.3,0.1

Type RM Length L Ch R = 1 ,10662.6 ,72.4,71.9,71.8
XS GIS Cut Line= 3
      1666115.83      731046.414     1666262.966      731203.966
     1666330.674      731407.091
#Sta/Elev= 28
       0  834.95     9.8  833.45    29.4  830.63      49  827.89    58.8  826.65
    68.6  825.89    78.4  825.68    88.2   825.3     101  821.71   107.8  819.76
   117.6  820.33   120.9821.5255   127.4  823.88   137.2  825.43     147  825.85
   215.6  828.22   254.5  829.35   283.7  830.11   303.2  830.79   322.6  831.21
   332.4  832.19   342.1   834.7   351.8   838.3   371.3  846.37   400.5  858.78
   410.2  861.99     420  863.73   429.7  864.71
#Mann= 3 , 0 , 0
       0      .1       0     101    .045       0   120.9      .1       0
Bank Sta=101,120.9
XS Rating Curve= 0 ,0
Exp/Cntr=0.3,0.1

Type RM Length L Ch R = 1 ,10590.7 ,198.9,230.8,261.6
XS GIS Cut Line= 4
     1666084.421      731053.879     1666124.207      731160.086
     1666160.665      731197.412     1666241.394      731316.336
#Sta/Elev= 26
       0  832.31     9.4  830.38    18.9  828.56    28.4   826.9    37.8   825.4
    47.3   824.3    56.7  823.75    66.2   823.6     104  823.64   113.4  823.45
   122.1  822.77   130.8  821.19   137.3  819.31   139.5  818.68   148.2  818.14
   152.3  819.15   156.9  820.29   165.6  823.18   175.2  824.92   223.1  827.58
   242.2  828.35   251.8  828.51     271  828.63   290.2  828.86   299.7   829.2
   309.3  830.85
#Mann= 3 , 0 , 0
       0      .1       0   137.3    .045       0   152.3      .1       0
Bank Sta=137.3,152.3
XS Rating Curve= 0 ,0
Exp/Cntr=0.3,0.1

Type RM Length L Ch R = 1 ,10360   ,72.3,62.6,52.6
XS GIS Cut Line= 4
     1666023.657      731036.518     1665994.216      731127.317
     1665941.264      731208.914     1665923.903      731302.664
#Sta/Elev= 28
       0  834.63    19.1  830.18    28.6  828.11    38.2  826.14    47.7  824.43
    57.3  823.33    66.8  822.87    85.9  822.57    95.4  821.86   105.2  820.25
   114.9  817.51   121.5  815.35   124.6  814.34   134.4  814.38   136.5  814.82
   144.1  816.42   153.8  818.74   163.5  820.65   173.3  822.04     183  823.15
   192.7  824.02   202.3  824.63   211.8  824.95   249.9  825.64   259.5  825.75
     269  826.22   278.5  827.17   288.1  828.28
#Mann= 3 , 0 , 0
       0     .06       0   121.5    .045       0   136.5     .06       0
Bank Sta=121.5,136.5
XS Rating Curve= 0 ,0
Exp/Cntr=0.3,0.1