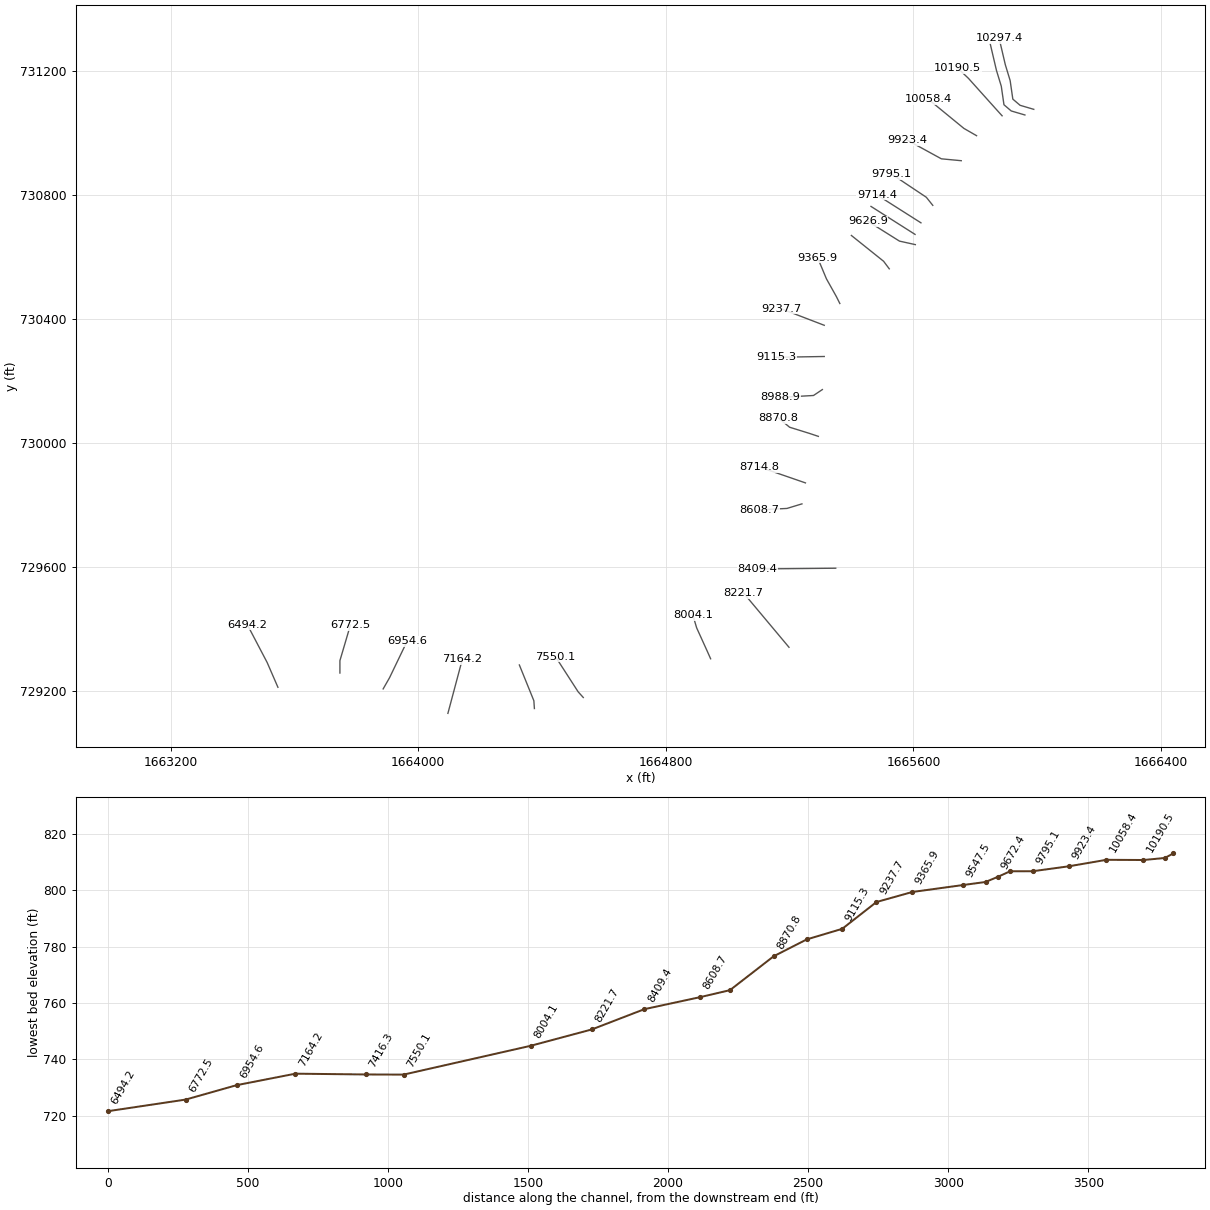
HEC-RAS study HARDINRUN.prj: HARDINRUN

--- HARDINRUN.g01 (geometry) --- (continued)

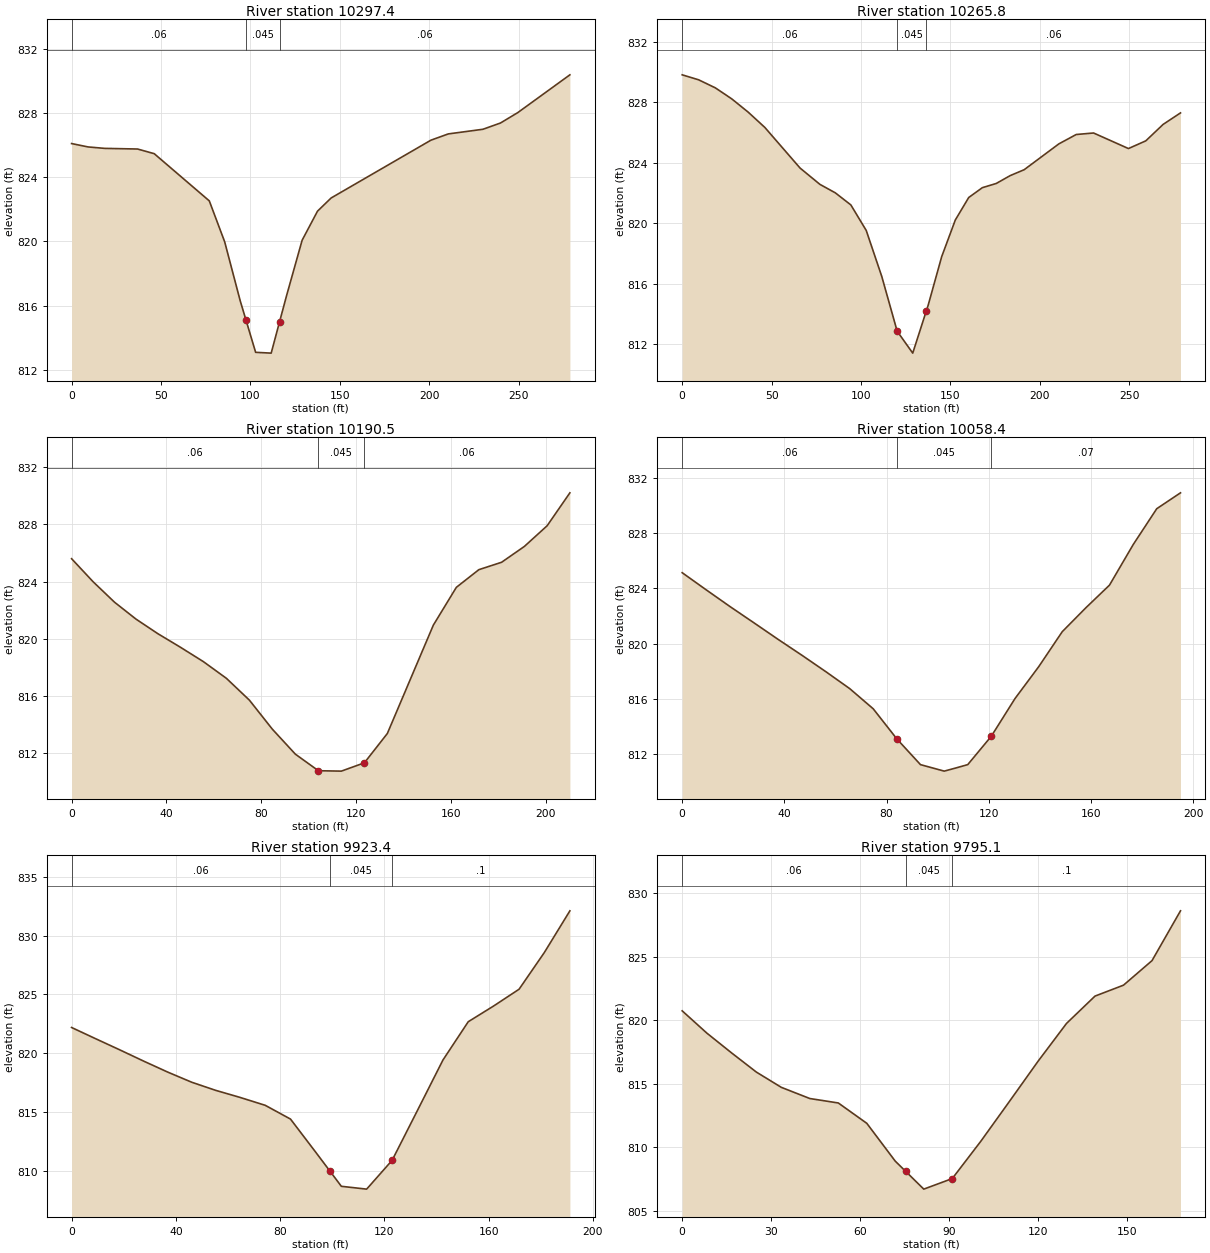
Type RM Length L Ch R = 1 ,10297.4 ,31.4,31.6,32.6
XS GIS Cut Line= 6
     1665989.007      731076.101     1665944.736      731089.122
     1665921.299      731109.088     1665912.618      731168.983
     1665896.993      731220.199     1665877.028      731305.268
#Sta/Elev= 22
       0  826.09     9.2  825.88    18.5  825.79    36.9  825.75    46.2  825.46
      77  822.52    85.6  819.97    94.3  816.29   97.52 815.094   102.9  813.09
   111.6  813.04   116.3     815   120.2  816.62   128.9  820.07   137.5  821.88
   145.1   822.7   200.9   826.3   210.6  826.69     230  826.98   239.8  827.37
   249.5  828.02   278.6  830.37
#Mann= 3 , 0 , 0
       0     .06       0   97.52    .045       0   116.3     .06       0
Bank Sta=97.52,116.3
XS Rating Curve= 0 ,0
Exp/Cntr=0.3,0.1

Type RM Length L Ch R = 1 ,10265.8 ,60.3,75.3,87.6
XS GIS Cut Line= 6
     1665960.361      731057.872     1665916.091      731070.893
     1665892.653      731090.858     1665883.972      731150.754
     1665868.347      731201.969     1665848.382      731287.039
#Sta/Elev= 30
       0  829.83     9.2   829.5    18.5  828.97    27.7  828.24    36.9  827.36
    46.2  826.35    65.9  823.66      77  822.58    85.6  822.02    94.3  821.22
   102.9  819.53   111.6  816.48   120.2  812.86   128.9  811.41   136.4  814.17
   137.5  814.57   145.1   817.8   152.7  820.22   160.2  821.71   167.8  822.36
   175.6  822.64   183.4  823.16   191.2  823.55   210.6  825.26   220.3  825.88
     230  825.98   249.5  824.95   259.2  825.46   268.9  826.55   278.6  827.31
#Mann= 3 , 0 , 0
       0     .06       0   120.2    .045       0   136.4     .06       0
Bank Sta=120.2,136.4
XS Rating Curve= 0 ,0
Exp/Cntr=0.3,0.1

Type RM Length L Ch R = 1 ,10190.5 ,130.4,132.1,135.5
XS GIS Cut Line= 4
     1665886.577      731055.268     1665862.271      731082.178
      1665778.07      731175.928     1665743.347      731208.914
#Sta/Elev= 25
       0   825.6     9.1  823.98    18.1  822.55    27.2  821.36    36.3  820.35
      46  819.38    55.6  818.38    65.3  817.21      75  815.68    84.7  813.64
    94.4  811.89   104.1  810.73   106.8  810.72   113.8   810.7   121.8  811.18
   123.5  811.28   133.2  813.34   142.9  817.14   152.6  820.94   162.3  823.59
   171.8  824.83   181.4  825.35     191  826.46   200.6  827.91   210.2  830.22
#Mann= 3 , 0 , 0
       0     .06       0   104.1    .045       0   123.5     .06       0
Bank Sta=104.1,123.5
XS Rating Curve= 0 ,0
Exp/Cntr=0.3,0.1

Type RM Length L Ch R = 1 ,10058.4 ,130.8,135.1,139.2
XS GIS Cut Line= 3
     1665804.111      730991.032     1665763.313      731014.469
     1665648.729      731108.219
#Sta/Elev= 24
       0  825.13     9.4  823.89    18.8  822.67    28.2  821.49    37.6   820.3
      47  819.14    56.3  817.96    65.6  816.74    74.8  815.28    84.1  813.09
    93.3  811.24   102.6  810.77     107  810.99   111.8  811.24   121.1  813.31
     122  813.58   130.3  816.02   139.6  818.33   148.8  820.86   158.1   822.6
   167.3  824.23   176.6  827.17   185.8  829.76   195.1  830.91
#Mann= 3 , 0 , 0
       0     .06       0    84.1    .045       0   121.1     .07       0
Bank Sta=84.1,121.1
XS Rating Curve= 0 ,0
Exp/Cntr=0.3,0.1

Type RM Length L Ch R = 1 ,9923.4  ,130.1,128.3,126.1
XS GIS Cut Line= 3
     1665754.632      730910.303     1665690.396      730916.379
     1665579.285      730977.143
#Sta/Elev= 23
       0  822.19     9.2  821.24    18.4   820.3    27.6  819.34    36.9   818.4
    46.1  817.54    55.3  816.85    64.5  816.26    74.3  815.58      84  814.41
    93.8  811.56    99.1     810   103.5   808.7   113.2  808.46   114.1  808.68
     123  810.91   132.7  815.14   142.5  819.43   152.2  822.68   161.9  824.01
   171.7  825.44   181.4  828.56   191.2   832.1
#Mann= 3 , 0 , 0
       0     .06       0    99.1    .045       0     123      .1       0
Bank Sta=99.1,123
XS Rating Curve= 0 ,0
Exp/Cntr=0.3,0.1

Type RM Length L Ch R = 1 ,9795.1  ,80.2,80.7,81.3
XS GIS Cut Line= 3
     1665662.618      730766.206     1665641.785      730792.247
     1665529.806        730866.9
#Sta/Elev= 21
       0  820.75     8.3     819    16.7  817.43      25  815.93    33.4  814.73
      43  813.85    52.6   813.5    62.2   811.9    71.8  808.92    75.3  808.12
    81.4  806.72    90.3  807.49      91  807.55   100.6  810.48   110.2   813.6
   119.9  816.78   129.5  819.76   139.1  821.91   148.7  822.77   158.3   824.7
   167.9  828.62
#Mann= 3 , 0 , 0
       0     .06       0    75.3    .045       0      91      .1       0
Bank Sta=75.3,91
XS Rating Curve= 0 ,0
Exp/Cntr=0.3,0.1

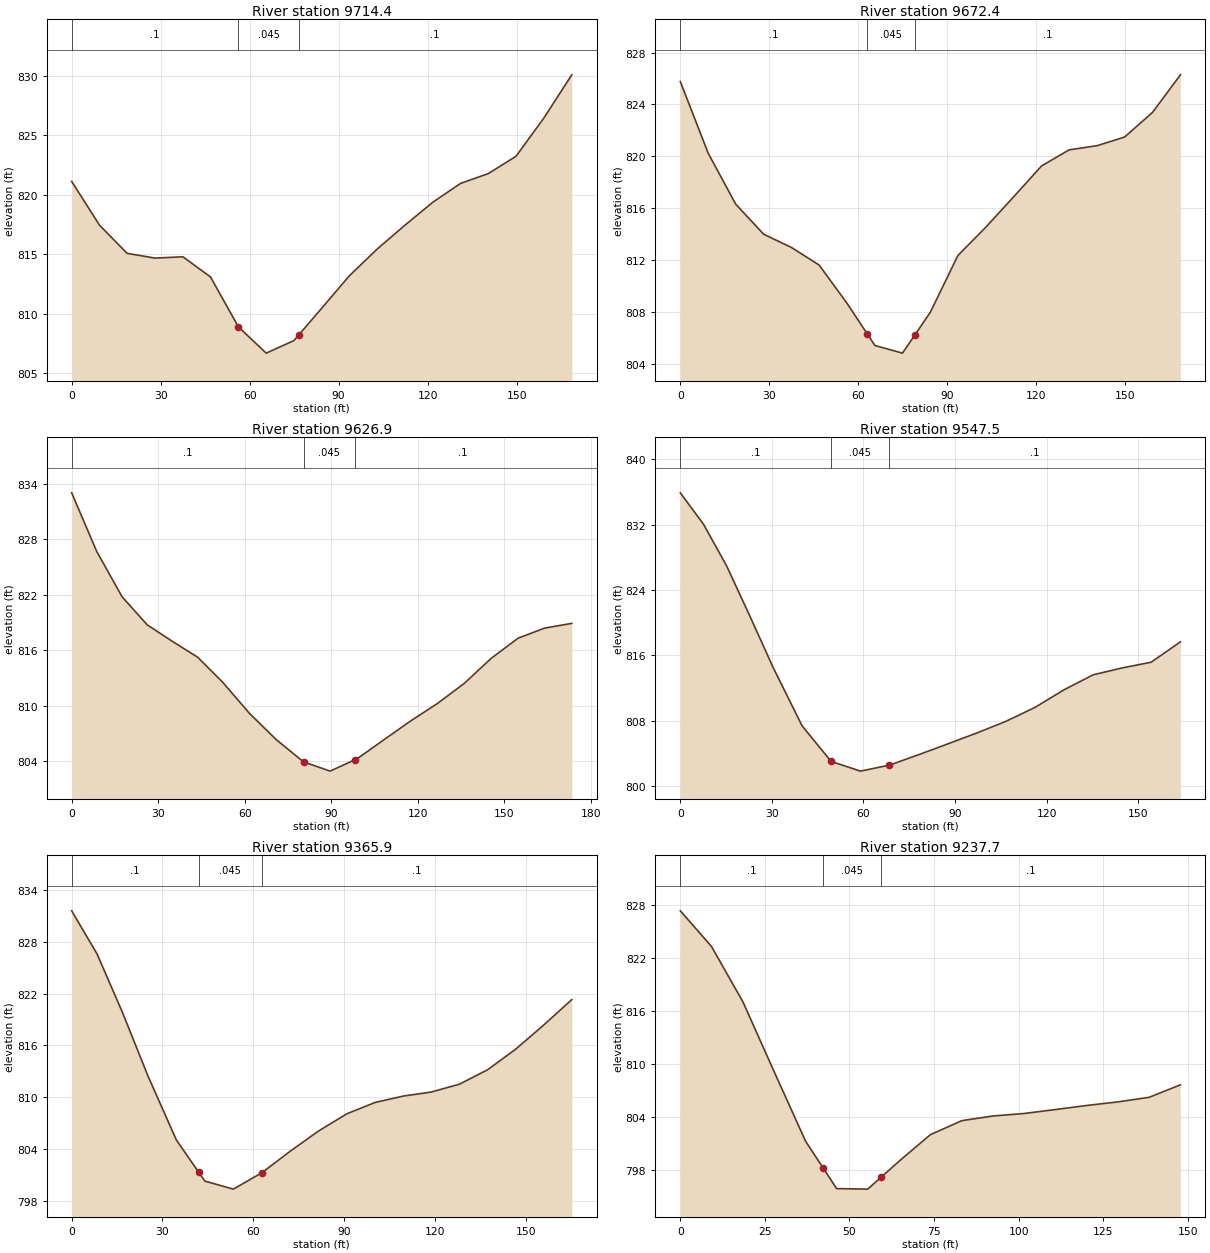
Type RM Length L Ch R = 1 ,9714.4  ,42,41.9,42
XS GIS Cut Line= 2
     1665624.424      730709.782     1665482.063       730800.06
#Sta/Elev= 21
       0  821.12     9.4  817.44    18.7  815.08    28.1  814.68    37.5  814.79
    46.8   813.1    56.2  808.91    61.5  807.66    65.6   806.7    74.9  807.75
    76.5  808.21    84.3  810.47    93.6  813.19     103  815.44   112.4  817.45
   121.8  819.38   131.1  820.95   140.5  821.78   149.8  823.23   159.2  826.44
   168.6  830.07
#Mann= 3 , 0 , 0
       0      .1       0    56.2    .045       0    76.5      .1       0
Bank Sta=56.2,76.5
XS Rating Curve= 0 ,0
Exp/Cntr=0.3,0.1

Type RM Length L Ch R = 1 ,9672.4  ,45.4,45.6,45.7
XS GIS Cut Line= 2
     1665605.327      730672.456     1665462.966      730762.733
#Sta/Elev= 22
       0  825.77     9.4  820.24    18.7   816.3    28.1  813.99    37.5  812.96
    46.8  811.61    56.2  808.66      63   806.3    65.6   805.4    74.9  804.81
      78  805.85   79.08806.2134    84.3  807.97    93.6  812.35     103  814.53
   112.4  816.88   121.8  819.26   131.1   820.5   140.5  820.82   149.8  821.49
   159.2  823.39   168.6  826.29
#Mann= 3 , 0 , 0
       0      .1       0      63    .045       0   79.08      .1       0
Bank Sta=63,79.08
XS Rating Curve= 0 ,0
Exp/Cntr=0.3,0.1

Type RM Length L Ch R = 1 ,9626.9  ,82,79.4,76.8
XS GIS Cut Line= 3
     1665606.195      730639.469     1665554.979      730650.754
     1665452.549       730714.99
#Sta/Elev= 22
       0  833.01     8.7  826.66    17.5  821.76    26.2  818.73      35  816.93
    43.7  815.23    52.4  812.51    61.7  809.14      71   806.3    80.4  803.91
    83.1  803.62    89.6  802.91    98.1  804.12      99  804.25   108.2  806.29
   117.6  808.35   126.8  810.22   136.2  812.42   145.4  815.09   154.8  817.29
     164  818.38   173.4  818.89
#Mann= 3 , 0 , 0
       0      .1       0    80.4    .045       0    98.1      .1       0
Bank Sta=80.4,98.1
XS Rating Curve= 0 ,0
Exp/Cntr=0.3,0.1

Type RM Length L Ch R = 1 ,9547.5  ,190.4,181.6,172.9
XS GIS Cut Line= 3
     1665521.993      730561.344     1665503.764       730585.65
     1665399.597      730668.983
#Sta/Elev= 21
       0  835.88     7.6  832.04    15.2  826.92    22.8  820.79    30.4  814.52
    39.9  807.37    49.4  803.03    53.2  802.56      59  801.84    68.2  802.55
    68.5  802.57      78  803.84    87.6  805.17    97.1   806.5   106.6  807.92
   116.1  809.62   125.7  811.79   135.2  813.62   144.7  814.46   154.2  815.16
   163.8  817.65
#Mann= 3 , 0 , 0
       0      .1       0    49.4    .045       0    68.2      .1       0
Bank Sta=49.4,68.2
XS Rating Curve= 0 ,0
Exp/Cntr=0.3,0.1

Type RM Length L Ch R = 1 ,9365.9  ,112.3,128.2,143.9
XS GIS Cut Line= 4
     1665362.271      730449.365     1665350.986      730471.935
     1665318.868      730529.226     1665290.222      730597.803
#Sta/Elev= 21
       0  831.59     8.4  826.59    16.8  819.81    25.2  812.47    34.6  805.05
    41.9  801.36      44   800.3    53.4  799.37    56.9  800.07    62.8  801.26
    72.2  803.76    81.5  806.09    90.9  808.09   100.2   809.4   109.5  810.14
   118.8  810.61   128.1  811.52   137.4  813.19   146.6  815.55   155.9  818.36
   165.2  821.31
#Mann= 3 , 0 , 0
       0      .1       0    41.9    .045       0    62.8      .1       0
Bank Sta=41.9,62.8
XS Rating Curve= 0 ,0
Exp/Cntr=0.3,0.1

Type RM Length L Ch R = 1 ,9237.7  ,113.6,122.4,130.9
XS GIS Cut Line= 2
     1665311.924      730379.053     1665173.903      730432.004
#Sta/Elev= 20
       0  827.35     9.2  823.32    18.5  817.04    27.7  809.15      37  801.26
    42.3  798.15    46.2  795.87    55.4  795.81    57.3  796.46   59.38797.1711
    64.7  798.99    73.9  801.98    83.2  803.57    92.4   804.1   101.6  804.38
   110.9  804.83   120.1  805.29   129.4   805.7   138.6  806.22   147.8  807.63
#Mann= 3 , 0 , 0
       0      .1       0    42.3    .045       0   59.38      .1       0
Bank Sta=42.3,59.38
XS Rating Curve= 0 ,0
Exp/Cntr=0.3,0.1

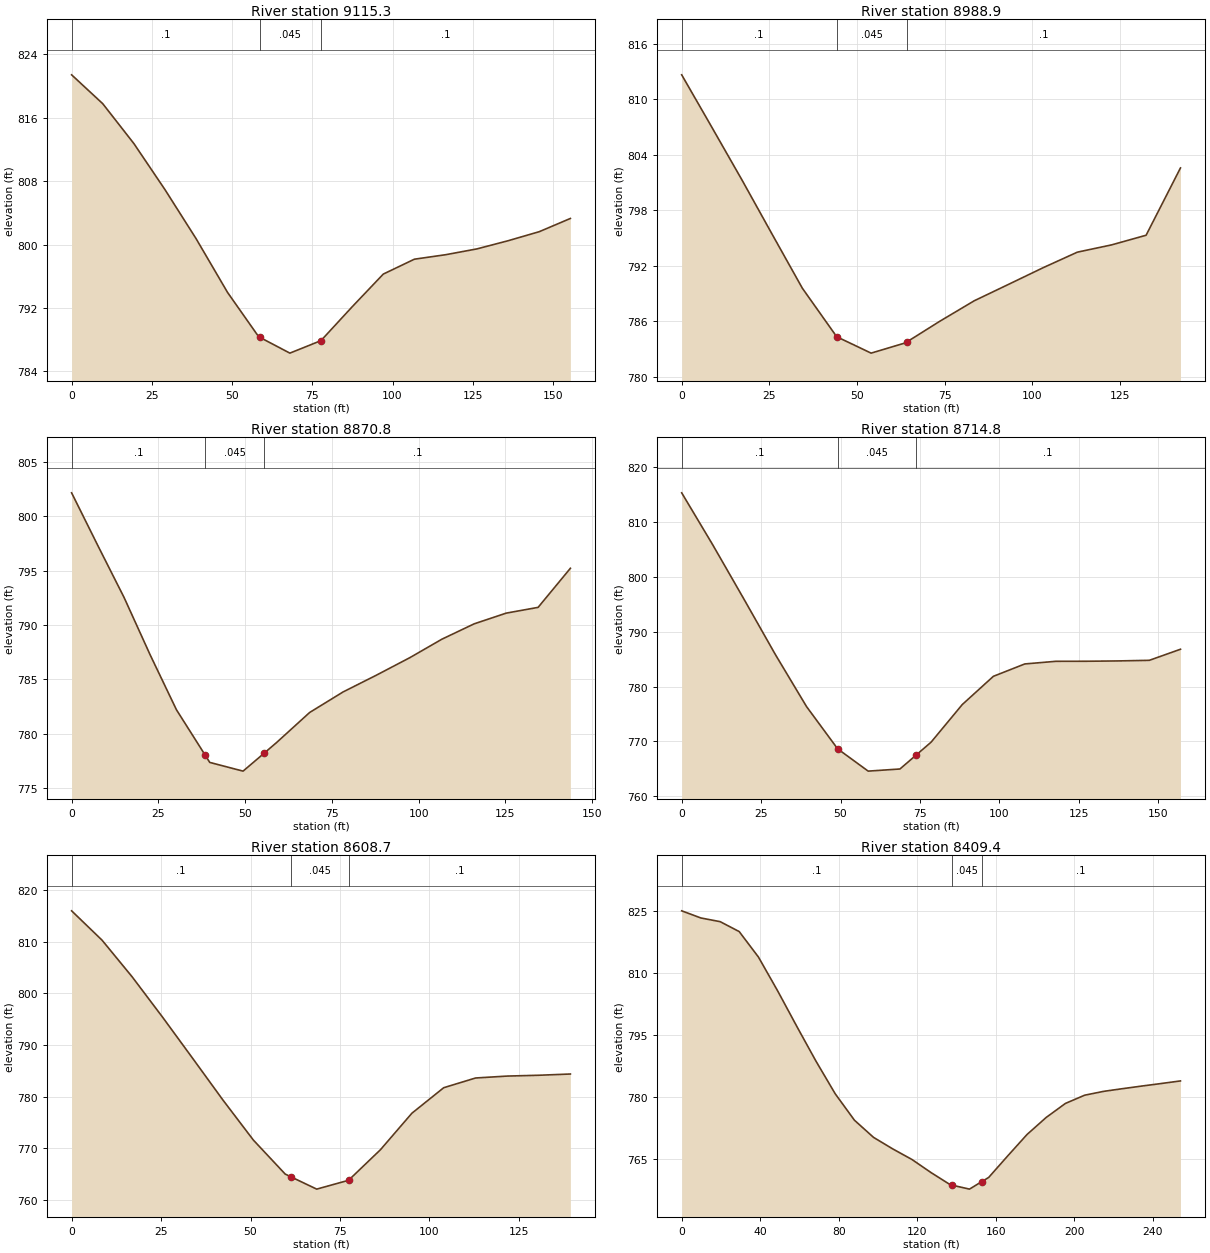
Type RM Length L Ch R = 1 ,9115.3  ,125.4,126.4,127.2
XS GIS Cut Line= 2
     1665311.924      730278.358     1665156.542      730275.754
#Sta/Elev= 19
       0  821.41     9.7  817.77    19.4  812.74    29.1  806.92    38.8  800.73
    48.6  793.95    58.3  788.36    58.6   788.3      68   786.3    73.6  787.21
    77.7  787.88    87.4  792.14    97.1  796.27   106.8  798.15   116.6  798.72
   126.3  799.45     136  800.48   145.7  801.62   155.4  803.29
#Mann= 3 , 0 , 0
       0      .1       0    58.6    .045       0    77.7      .1       0
Bank Sta=58.6,77.7
XS Rating Curve= 0 ,0
Exp/Cntr=0.3,0.1

Type RM Length L Ch R = 1 ,8988.9  ,126.4,118.1,110
XS GIS Cut Line= 3
     1665305.847      730171.588     1665277.202       730152.49
     1665169.563      730146.414
#Sta/Elev= 18
       0  812.66     8.6  806.99    17.2  801.28    25.8  795.41    34.4  789.58
    44.2  784.33    49.2  783.43      54  782.56    63.8  783.67    64.2  783.77
    73.6  786.01    83.4  788.22    93.2     790     103  791.79   112.8  793.48
   122.6  794.27   132.4  795.31   142.2  802.59
#Mann= 3 , 0 , 0
       0      .1       0    44.2    .045       0    64.2      .1       0
Bank Sta=44.2,64.2
XS Rating Curve= 0 ,0
Exp/Cntr=0.3,0.1

Type RM Length L Ch R = 1 ,8870.8  ,156.4,156,155.2
XS GIS Cut Line= 4
     1665292.827      730020.546     1665264.181      730030.094
     1665199.945       730050.06     1665164.354      730079.574
#Sta/Elev= 20
       0  802.14     7.6  797.27    15.1  792.54    22.6  787.28    30.2  782.22
    38.5  778.04    39.8  777.38    49.4  776.58    53.5  777.69   55.55778.2491
      59  779.19    68.6  781.97    78.2  783.85    87.8  785.39    97.5  787.01
   106.7   788.7     116  790.11   125.2  791.09   134.4  791.62   143.7  795.21
#Mann= 3 , 0 , 0
       0      .1       0    38.5    .045       0   55.55      .1       0
Bank Sta=38.5,55.55
XS Rating Curve= 0 ,0
Exp/Cntr=0.3,0.1

Type RM Length L Ch R = 1 ,8714.8  ,95.7,106.2,114.6
XS GIS Cut Line= 2
      1665251.16      729870.372     1665102.722      729921.588
#Sta/Elev= 18
       0  815.33     9.8  805.82    19.6  795.94    29.4  785.92    39.3  776.34
    49.1  768.63    58.7  764.57    68.7  764.96    73.7  767.45    78.5  769.85
    88.3   776.7    98.1  781.86     108  784.12   117.8   784.6   127.6  784.61
   137.4  784.67   147.2  784.78     157   786.8
#Mann= 3 , 0 , 0
       0      .1       0    49.1    .045       0    73.7      .1       0
Bank Sta=49.1,73.7
XS Rating Curve= 0 ,0
Exp/Cntr=0.3,0.1

Type RM Length L Ch R = 1 ,8608.7  ,201.8,199.3,198.3
XS GIS Cut Line= 3
     1665239.875      729802.664     1665191.264      729787.907
     1665102.722      729783.567
#Sta/Elev= 19
       0  815.94     8.5  810.27    16.9  803.19    25.4  795.39    33.9  787.34
    42.3  779.33    50.8  771.59    59.7  765.01    61.2  764.51    68.5   762.1
    76.2  763.58    77.4  763.81    86.3  769.71    95.1  776.78     104  781.72
   112.9   783.6   121.7  783.97   130.6  784.13   139.4  784.37
#Mann= 3 , 0 , 0
       0      .1       0    61.2    .045       0    77.4      .1       0
Bank Sta=61.2,77.4
XS Rating Curve= 0 ,0
Exp/Cntr=0.3,0.1

Type RM Length L Ch R = 1 ,8409.4  ,208.2,187.7,167.3
XS GIS Cut Line= 2
     1665349.033       729594.96      1665094.91      729592.594
#Sta/Elev= 29
       0  825.14     9.8  823.41    19.6  822.52    29.3  820.12    39.1  813.96
    48.9  805.77    58.6  797.23    68.4  788.79    78.2   780.9      88   774.5
    97.7  770.36   107.5  767.56   117.3     765   127.1  761.81   136.8   758.9
   137.8  758.79   146.6  757.83   152.8  759.62   156.4  760.66   166.2  765.92
   175.9  771.03   185.7  775.17   195.5  778.56   205.3  780.55     215  781.48
   224.8  782.14   234.6  782.77   244.4  783.38   254.1     784
#Mann= 3 , 0 , 0
       0      .1       0   137.8    .045       0   152.8      .1       0
Bank Sta=137.8,152.8
XS Rating Curve= 0 ,0
Exp/Cntr=0.3,0.1

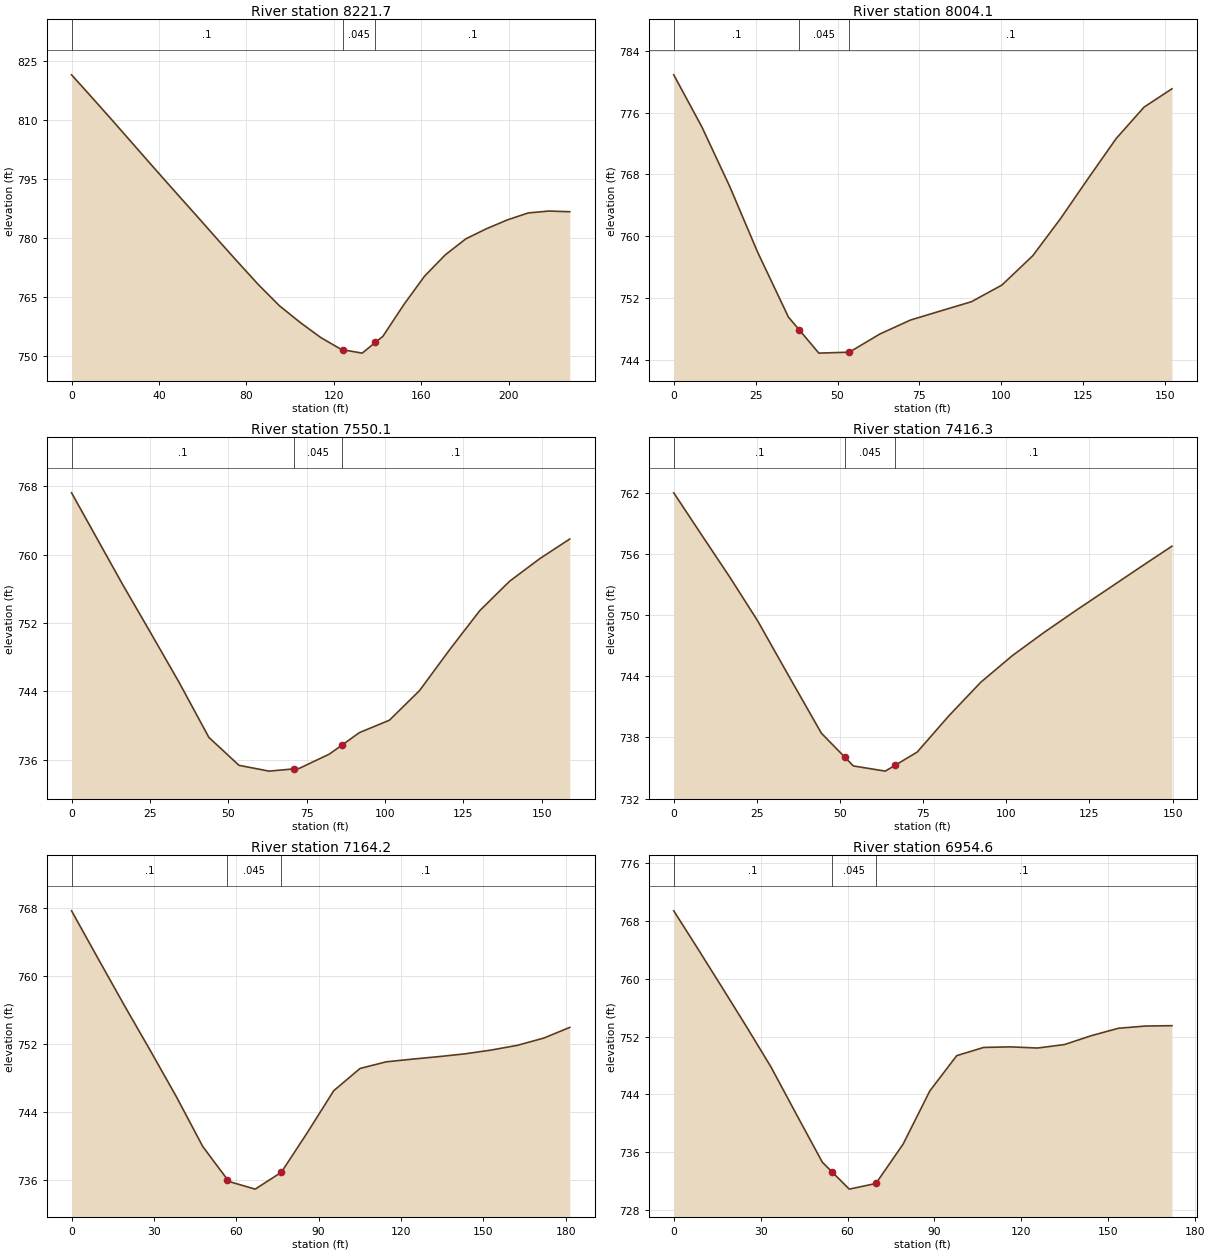
Type RM Length L Ch R = 1 ,8221.7  ,223.8,217.6,211.9
XS GIS Cut Line= 2
     1665197.992      729339.752     1665051.507      729514.469
#Sta/Elev= 27
       0  821.45     9.5  815.58      19  809.64    28.5  803.62      38   797.6
    47.5  791.64      57  785.74    66.5  779.76      76  773.86    85.5  768.07
      95  762.76   104.5   758.5     114  754.62   123.5  751.56     124  751.51
     133  750.64     139  753.35   142.5  754.93     152  762.93   161.5  770.19
     171  775.63   180.5  779.74     190  782.32   199.5  784.55     209  786.31
   218.5  786.79     228  786.62
#Mann= 3 , 0 , 0
       0      .1       0     124    .045       0     139      .1       0
Bank Sta=124,139
XS Rating Curve= 0 ,0
Exp/Cntr=0.3,0.1

Type RM Length L Ch R = 1 ,8004.1  ,450.2,454,456.4
XS GIS Cut Line= 4
     1664944.736      729302.664      1664934.32      729326.101
     1664899.597       729402.49     1664887.445      729443.289
#Sta/Elev= 20
       0  780.91     8.6  774.15    17.1  766.44    25.6  757.95      35  749.54
    38.3  747.88    44.3  744.86    53.3  744.98    53.6  744.98    62.9  747.33
    72.3  749.15    81.6  750.34    90.9  751.52   100.2  753.68   109.6  757.47
   118.1  762.29   126.6  767.53   135.1  772.67   143.6  776.73   152.1   779.1
#Mann= 3 , 0 , 0
       0      .1       0    38.3    .045       0    53.6      .1       0
Bank Sta=38.3,53.6
XS Rating Curve= 0 ,0
Exp/Cntr=0.3,0.1

Type RM Length L Ch R = 1 ,7550.1  ,138.2,133.8,129.7
XS GIS Cut Line= 3
     1664533.278      729177.664     1664516.785      729195.893
     1664443.868       729308.74
#Sta/Elev= 20
       0  767.24     8.2  761.83    16.4  756.43    24.6  751.24    34.2   745.1
    43.8  738.59    53.4  735.32      63  734.64    71.1  734.91    72.6  734.96
    82.2  736.63    86.1  737.65    91.8  739.15   101.4  740.61     111  744.08
   120.6  748.87   130.2  753.44   139.7  756.88   149.3  759.52   158.9  761.83
#Mann= 3 , 0 , 0
       0      .1       0    71.1    .045       0    86.1      .1       0
Bank Sta=71.1,86.1
XS Rating Curve= 0 ,0
Exp/Cntr=0.3,0.1

Type RM Length L Ch R = 1 ,7416.3  ,266.5,252.1,237.3
XS GIS Cut Line= 3
     1664375.292      729142.074     1664373.556      729167.247
     1664326.681      729282.699
#Sta/Elev= 19
       0  762.01     8.4  757.87    16.8  753.76    25.2  749.46    34.8  743.91
    44.4  738.41    51.5  736.04      54   735.2    63.6  734.69    66.5  735.25
    73.2  736.56    82.7  740.11    92.3  743.41   101.9  746.05   111.5  748.34
   121.1   750.5   130.7   752.6   140.2  754.69   149.8  756.77
#Mann= 3 , 0 , 0
       0      .1       0    51.5    .045       0    66.5      .1       0
Bank Sta=51.5,66.5
XS Rating Curve= 0 ,0
Exp/Cntr=0.3,0.1

Type RM Length L Ch R = 1 ,7164.2  ,214,209.7,205.4
XS GIS Cut Line= 2
     1664095.778      729126.449     1664142.653      729301.796
#Sta/Elev= 22
       0   767.7     9.6  762.12    19.1  756.65    28.7  751.26    38.2  745.83
    47.8  739.98    56.8  736.09    57.3  735.87    66.9  734.97    71.8  735.99
    76.4  736.94      86  741.67    95.5  746.54   105.1  749.16   114.6  749.94
   124.2  750.26   133.7  750.55   143.3  750.88   152.8  751.32   162.4  751.88
     172  752.73   181.5  753.99
#Mann= 3 , 0 , 0
       0      .1       0    56.8    .045       0    76.4      .1       0
Bank Sta=56.8,76.4
XS Rating Curve= 0 ,0
Exp/Cntr=0.3,0.1

Type RM Length L Ch R = 1 ,6954.6  ,178.1,182,185.7
XS GIS Cut Line= 3
     1663886.577      729205.442      1663907.41        729241.9
     1663963.834      729359.088
#Sta/Elev= 21
       0  769.38     8.4  764.09    16.8  758.72    25.2  753.31    33.6  747.77
      42   741.5    51.3  734.62    54.8  733.22    60.6   730.9    69.8  731.68
    79.2  737.13    88.4  744.47    97.7  749.36     107  750.49   116.3  750.57
   125.6  750.41   134.9  750.89   144.2  752.12   153.5  753.14   162.8  753.45
     172   753.5
#Mann= 3 , 0 , 0
       0      .1       0    54.8    .045       0    69.8      .1       0
Bank Sta=54.8,69.8
XS Rating Curve= 0 ,0
Exp/Cntr=0.3,0.1

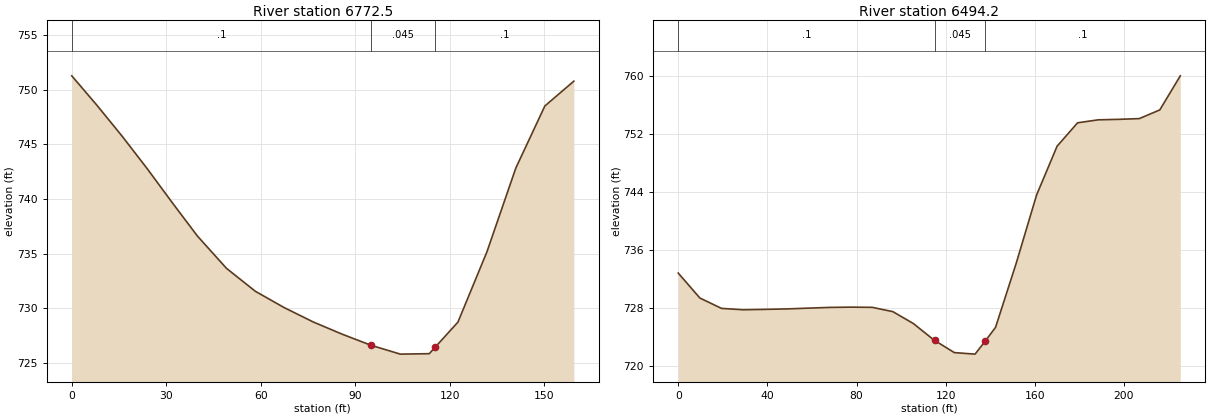
Type RM Length L Ch R = 1 ,6772.5  ,260.9,278.4,295.7
XS GIS Cut Line= 3
      1663746.82      729256.657      1663746.82      729296.588
     1663780.674      729411.171
#Sta/Elev= 21
       0  751.27       8  748.57      16  745.74      24  742.75      32  739.62
    39.9   736.6    49.1  733.65    58.3  731.54    67.5  730.04    76.7  728.73
    85.9  727.61    95.1  726.59   100.3  726.14   104.3  725.79   113.5  725.83
   115.3   726.4   122.6  728.72   131.8  735.15     141  742.84   150.2  748.51
   159.4  750.78
#Mann= 3 , 0 , 0
       0      .1       0    95.1    .045       0   115.3      .1       0
Bank Sta=95.1,115.3
XS Rating Curve= 0 ,0
Exp/Cntr=0.3,0.1

Type RM Length L Ch R = 1 ,6494.2  ,6500.3,6494.2,6483.5
XS GIS Cut Line= 3
     1663546.516       729210.65     1663511.794      729290.511
     1663447.558      729412.907
#Sta/Elev= 28
       0  732.84     9.7   729.4    19.4  727.97      29  727.78    38.7  727.83
    48.4  727.89    58.1     728    67.7   728.1    77.4  728.14    87.1  728.11
    96.3  727.52   105.5  725.88   114.7  723.62     115  723.56   123.9  721.87
     130  721.73   133.2  721.66  137.73  723.44   142.4  725.36   151.6  734.13
   160.8   743.6     170  750.33   179.2  753.56   188.4  753.97   197.7  754.04
   206.9  754.14   216.1  755.34   225.3  760.04
#Mann= 3 , 0 , 0
       0      .1       0     115    .045       0  137.73      .1       0
Bank Sta=115,137.73
XS Rating Curve= 0 ,0
Exp/Cntr=0.3,0.1

Chan Stop Cuts=-1
Use User Specified Reach Order=0
Composite Channel Slope=5